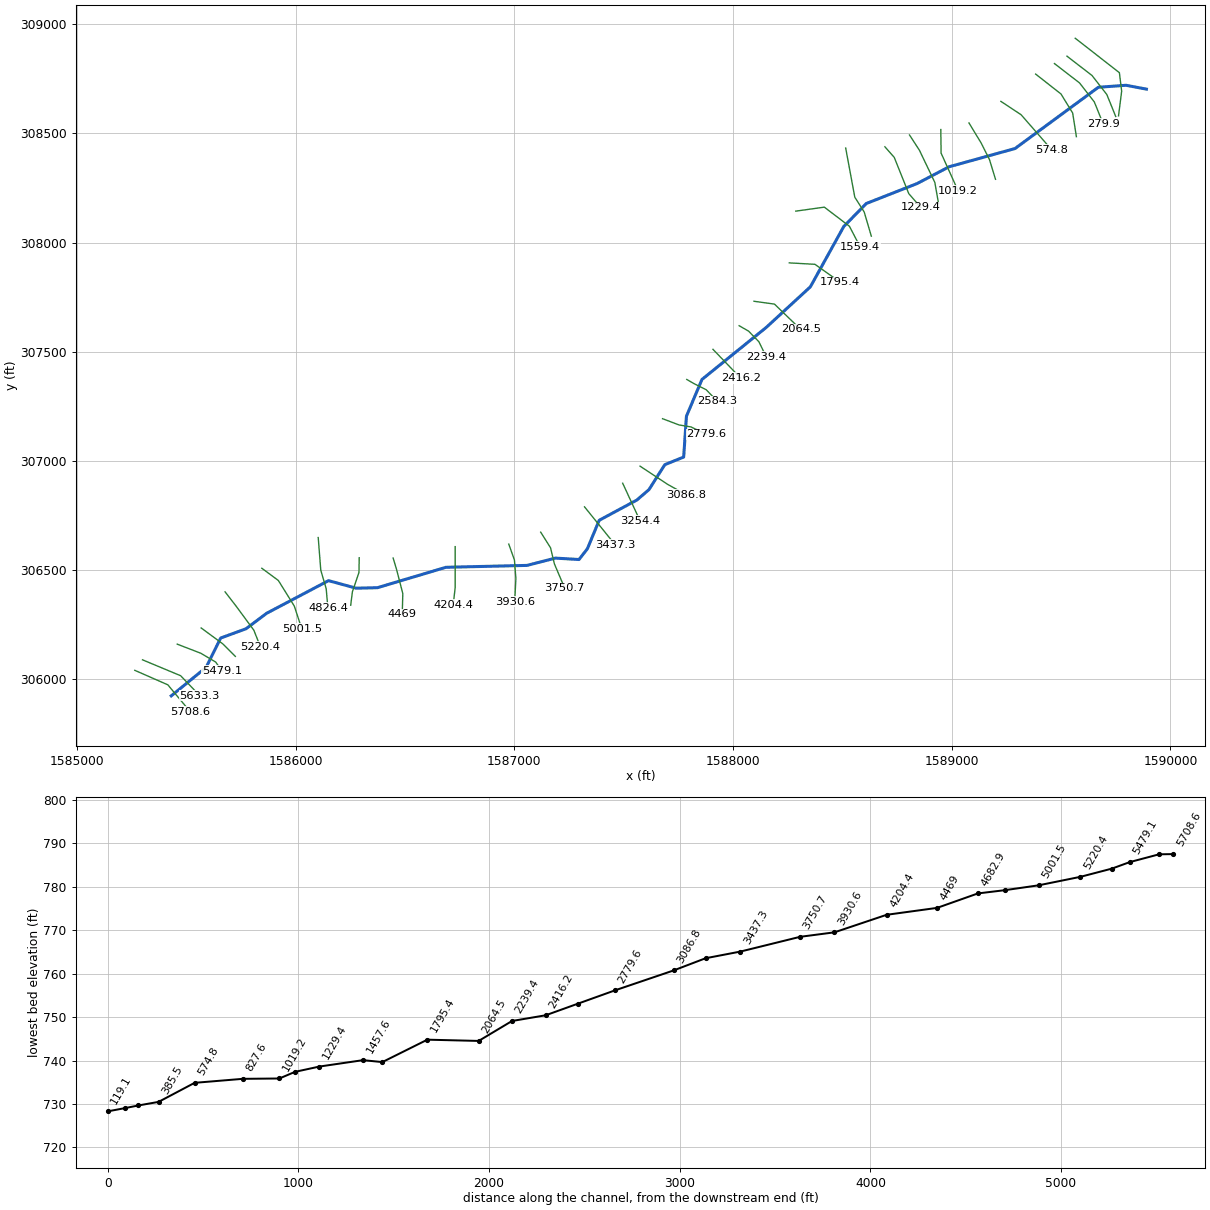
--- SHORTRN.prj (project) ---

Proj Title=SHORTRN
Current Plan=p01
Default Exp/Contr=0,0
English Units
Geom File=g01
Geom File=g02
Flow File=f01
Plan File=p01
BEGIN DESCRIPTION:
END DESCRIPTION:
DSS Export Rating Curves= 0
DSS Export Rating Curve Sorted= 0
DSS Export Volume Flow Curves= 0
DXF OffsetX= 0
DXF OffsetY= 0
DXF ScaleX= 0
DXF ScaleY= 0

--- SHORTRN.p01 (plan) ---

Plan Title=Floodplain
Program Version=4.00
Geom File=g01
Flow File=f01
K Sum by GR=0
Std Step Tol=0.01
Critical Tol=0.01
Num of Std Step Trials=20
Max Error Tol=0.3
Flow Tol Ratio=0.001
Split Flow NTrial=30
Split Flow Tol=0.02
Split Flow Ratio=0.02
Log Output Level=0
Friction Slope Method=1
Unsteady Friction Slope Method=2
Unsteady Bridges Friction Slope Method=1
Global Log Level=0
CheckData=False
Run HTab=0
Run UNet=0
Run PostProcess=0
UNET Theta=0
UNET Theta Warmup=0
UNET ZTol=0
UNET ZSATol=0
UNET MxIter=0
UNET MaxInSteps=0
UNET DtIC=0
UNET DtMin=0
UNET MaxCRTS=0
UNET WFStab=0
UNET SFStab=0
UNET WFX=0
UNET SFX=0
UNET DSS MLevel=0
UNET DZMax Abort=0
UNET Convert EG Bridges=0
UNET Use Existing IB Tables=0
UNET Froude Limit=0
UNET Froude Power=0
Write IC File=0
Echo Input=False
Echo Output=False
Write Detailed=0

--- SHORTRN.f01 (steady flow) ---

Flow Title=NFF Regression Equation
Program Version=4.10
Number of Profiles= 1
Profile Names=P100yr
River Rch & RM=SHORTRN,Main            ,5708.6
889.2982
River Rch & RM=SHORTRN,Main            ,4826.4
941.9756
River Rch & RM=SHORTRN,Main            ,1457.6
1021.092
River Rch & RM=SHORTRN,Main            ,1101.5
1344.106
River Rch & RM=SHORTRN,Main            ,574.8
1348.328
Boundary for River Rch & Prof#=SHORTRN,Main            , 1
Up Type= 0
Dn Type= 3
Dn Slope=0.0085
DSS Import GetInterval= 0
DSS Import GetPeak= 0
DSS Import FillOption= 0

--- SHORTRN.g01 (geometry) ---

Geom Title=USGS 10m DEM
Program Version=4.10

River Reach=SHORTRN         ,Main
Reach XY= 30
     1585431.838       305924.05     1585591.207      306054.532
     1585657.781      306188.894     1585773.935      306231.515
     1585867.906      306302.258     1586150.876      306451.767
     1586277.549      306417.131     1586374.506      306419.458
     1586687.659       306512.88      1587058.24      306521.572
     1587188.178      306554.955     1587296.066      306548.508
     1587334.338      306597.715     1587388.308      306728.108
     1587560.554      306820.896     1587615.955      306868.733
     1587688.246      306982.838     1587774.593      307017.822
     1587787.179      307204.888     1587858.143      307373.074
      1588152.22      307611.591     1588353.671      307797.185
     1588506.363      308073.377     1588609.237      308178.722
     1588841.554      308270.142     1588988.297      308347.159
      1589289.35      308430.582     1589670.349      308711.141
     1589796.778      308720.319      1589890.05       308702.64

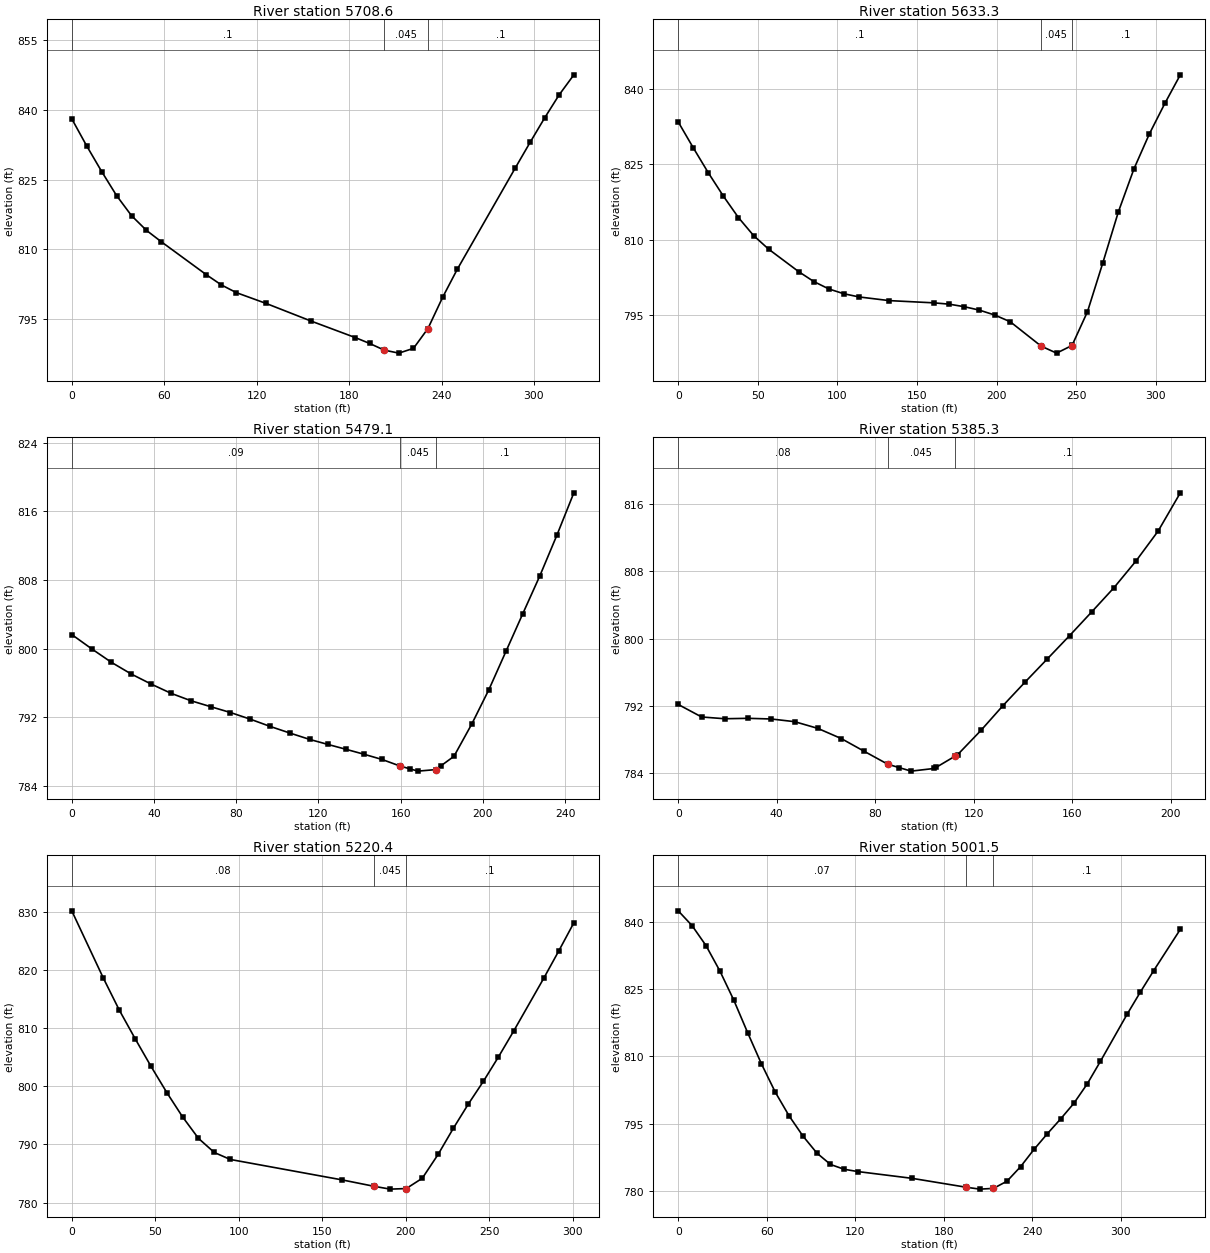
Type RM Length L Ch R = 1 ,5708.6  ,73.4,75.3,76.5
XS GIS Cut Line= 3
     1585265.228       306041.07     1585416.269      305974.664
     1585519.134      305850.966
#Sta/Elev= 25
       0   838.1     9.7  832.24    19.4  826.73    29.1  821.53    38.8   817.2
    48.5  814.03    58.2  811.56    87.4  804.46    97.1  802.27   106.8  800.61
   126.2  798.27   155.3  794.48   183.9  790.93   193.4  789.64   202.8  788.21
   212.3  787.56   221.8  788.59   231.2  792.87   240.7  799.58   250.2  805.62
     288  827.56   297.5  833.01     307  838.32   316.4  843.28   325.9  847.58
#Mann= 3 , 0 , 0
       0      .1       0   202.8    .045       0   231.2      .1       0
Bank Sta=202.8,231.2
XS Rating Curve= 0 ,0
Exp/Cntr=0.3,0.1

Type RM Length L Ch R = 1 ,5633.3  ,148.1,154.2,160.2
XS GIS Cut Line= 3
     1585300.384      306089.247     1585474.863       306016.33
     1585562.103      305925.185
#Sta/Elev= 30
       0  833.41     9.5  828.25    18.9  823.31    28.4  818.66    37.8  814.43
    47.3  810.86    56.7  808.17    75.6   803.7    85.1  801.73    94.6  800.25
     104   799.3   113.5  798.67   132.4  797.94   160.7  797.49   170.2  797.23
   179.6  796.73   189.1  796.05   198.8  795.07   208.5  793.74   227.9   788.9
   237.6  787.51     247 788.983   247.3  789.03     257  795.74   266.7   805.5
   276.4  815.56   286.2  824.11   295.9  831.06   305.6   837.1   315.3  842.77
#Mann= 3 , 0 , 0
       0      .1       0   227.9    .045       0     247      .1       0
Bank Sta=227.9,247
XS Rating Curve= 0 ,0
Exp/Cntr=0.3,0.1

Type RM Length L Ch R = 1 ,5479.1  ,95.7,93.8,91.3
XS GIS Cut Line= 4
     1585459.238      306160.862     1585567.311      306119.195
     1585635.019       306078.83     1585663.665      306038.466
#Sta/Elev= 30
       0  801.63     9.6  799.98    19.3  798.39      29  797.02    38.6  795.86
    48.3  794.78    57.9  793.92    67.6  793.22    77.2  792.54    86.9  791.76
    96.5  790.92   106.2  790.14   115.8   789.4   124.6  788.82   133.3  788.26
   142.1  787.68   150.9  787.07   159.6  786.31   164.4  785.98   168.4  785.71
   177.1  785.89   179.4   786.3   185.9  787.44   194.6  791.22   202.9  795.22
   211.2  799.68   219.4  804.08   227.6  808.44   235.9  813.18   244.2  818.15
#Mann= 3 , 0 , 0
       0     .09       0   159.6    .045       0   177.1      .1       0
Bank Sta=159.6,177.1
XS Rating Curve= 0 ,0
Exp/Cntr=0.3,0.1

Type RM Length L Ch R = 1 ,5385.3  ,171.3,164.9,157.3
XS GIS Cut Line= 3
     1585568.613       306235.08     1585667.571      306162.164
     1585724.863      306104.872
#Sta/Elev= 26
       0  792.15     9.5  790.66    18.9  790.45    28.4   790.5    37.8  790.42
    47.3   790.1    56.7   789.3    66.2  788.09    75.6  786.56    85.1  785.03
    89.7  784.63    94.6  784.21     104  784.53   104.7  784.65   112.2 785.954
   113.5  786.18   122.9  789.05   131.9  792.02   140.9  794.83   149.9  797.58
   158.9  800.34   167.9  803.17   176.9  806.04   185.9  809.24   194.9  812.81
   203.9  817.36
#Mann= 3 , 0 , 0
       0     .08       0    85.1    .045       0   112.2      .1       0
Bank Sta=85.1,112.2
XS Rating Curve= 0 ,0
Exp/Cntr=0.3,0.1

Type RM Length L Ch R = 1 ,5220.4  ,220.4,218.9,217
XS GIS Cut Line= 4
     1585677.988      306400.445     1585730.071      306332.737
     1585809.499      306224.664     1585839.446      306149.143
#Sta/Elev= 24
       0  830.18      19  818.56    28.5  813.09      38  808.17    47.5  803.42
      57   798.9    66.4  794.74    75.9  791.05    85.4  788.62      95  787.42
   162.1   783.9   181.2   782.8   190.8  782.32   200.4782.4185     210  784.19
   219.5   788.3   228.6  792.78   237.6  796.96   246.6  800.86   255.6  805.04
   264.7  809.48   282.7  818.55   291.8   823.3   300.8  828.12
#Mann= 3 , 0 , 0
       0     .08       0   181.2    .045       0   200.4      .1       0
Bank Sta=181.2,200.4
XS Rating Curve= 0 ,0
Exp/Cntr=0.3,0.1

Type RM Length L Ch R = 1 ,5001.5  ,180.8,175.1,168.4
XS GIS Cut Line= 4
     1585845.957      306508.518     1585921.478      306452.528
     1585994.394      306335.341     1586028.249      306232.476
#Sta/Elev= 30
       0  842.41     9.4   839.1    18.8  834.67    28.2  829.02    37.6  822.54
      47  815.28    56.4  808.29    65.8  801.97    75.2  796.67    84.6  792.17
      94   788.4   103.2  785.87   112.4   784.8   121.6  784.29   158.4  782.78
   195.2  780.79   204.4  780.37   213.6  780.53   222.8  782.13     232  785.36
   241.1  789.21   250.1  792.69   259.1  795.99   268.1  799.48   277.2  803.82
   286.2  808.89   304.2  819.33   313.2  824.29   322.3   829.1   340.3  838.28
#Mann= 3 , 0 , 0
       0     .07       0   195.2    .045       0   213.6      .1       0
Bank Sta=195.2,213.6
XS Rating Curve= 0 ,0
Exp/Cntr=0.3,0.1

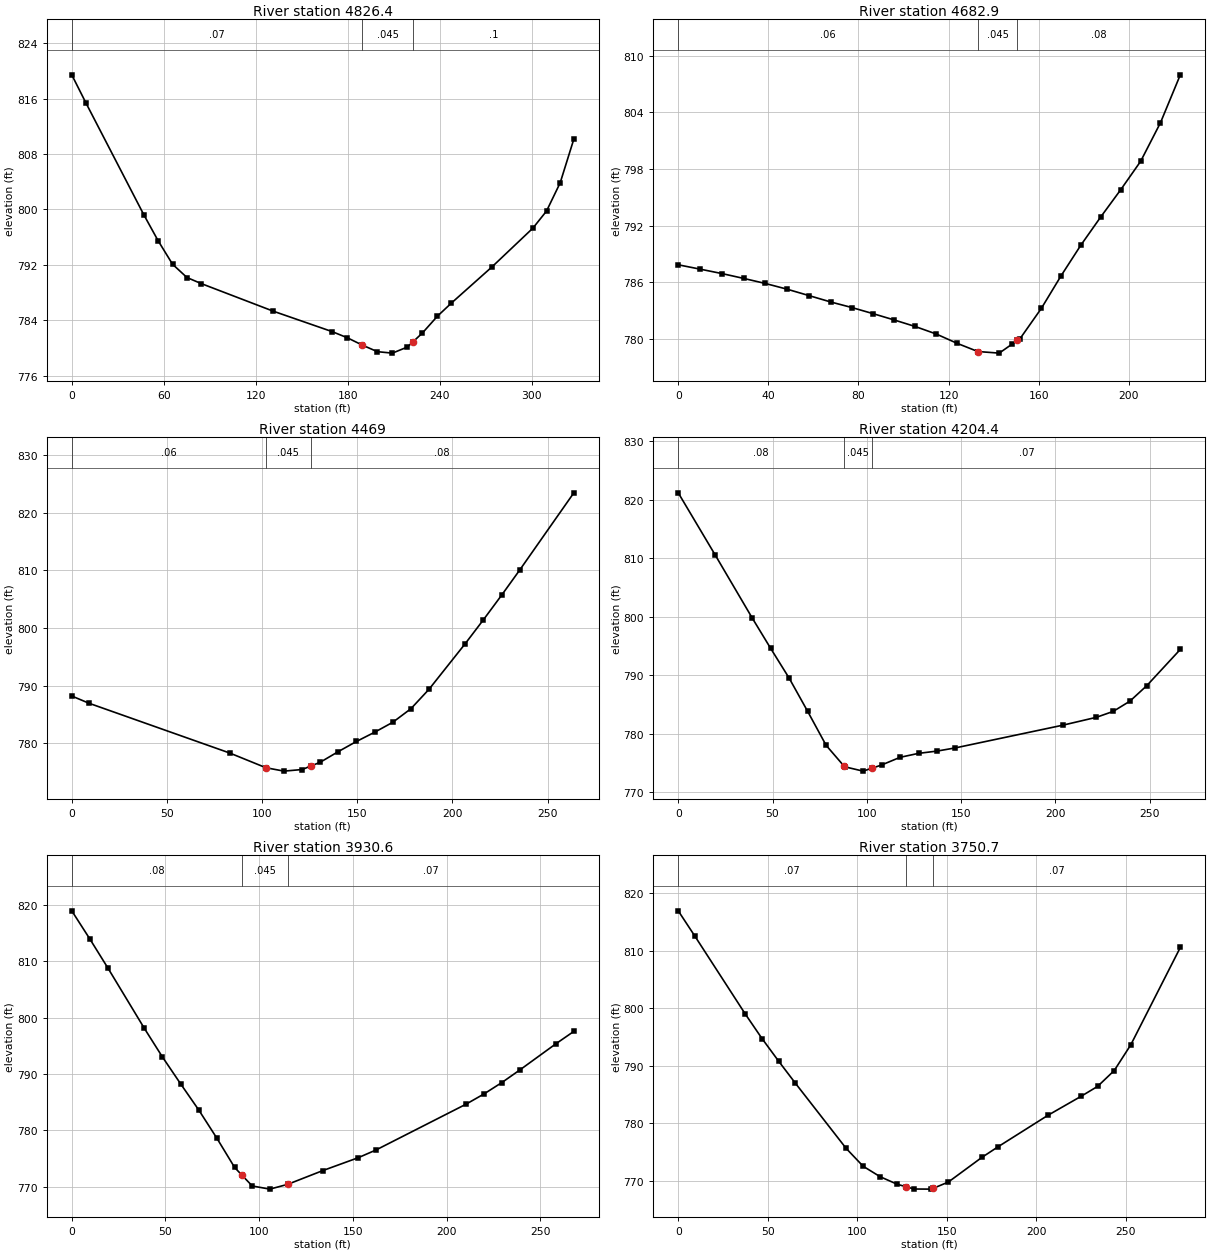
Type RM Length L Ch R = 1 ,4826.4  ,157.5,143.5,129.8
XS GIS Cut Line= 4
     1586103.769      306649.143     1586115.488      306499.403
     1586140.228      306414.768      1586148.04      306326.226
#Sta/Elev= 23
       0  819.43     9.4   815.3    46.9  799.26    56.3  795.48    65.7  792.09
    75.1  790.17    84.5  789.29   131.4  785.31   169.8  782.36   179.6  781.48
   189.4  780.42   199.2  779.47     209  779.26   218.8  780.14   222.4780.8857
   228.6  782.17   238.4   784.6   247.3  786.45   273.9   791.7   300.6   797.3
   309.5  799.77   318.4  803.85   327.3  810.16
#Mann= 3 , 0 , 0
       0     .07       0   189.4    .045       0   222.4      .1       0
Bank Sta=189.4,222.4
XS Rating Curve= 0 ,0
Exp/Cntr=0.3,0.1

Type RM Length L Ch R = 1 ,4682.9  ,200.8,214,226.6
XS GIS Cut Line= 4
     1586291.269      306556.695     1586289.967      306488.987
     1586260.019      306400.445     1586252.207      306339.247
#Sta/Elev= 28
       0  787.86     9.7   787.4    19.4  786.93      29  786.42    38.7  785.88
    48.4  785.27      58   784.6    67.7  783.92    77.1  783.33    86.4  782.69
    95.8  782.02   105.1  781.33   114.5  780.53   123.8  779.54     133  778.67
   133.2778.6664   142.5   778.5     148  779.42   150.6 779.851   151.8  780.05
   161.2  783.24     170  786.71   178.8  789.96   187.6  792.94   196.4   795.8
   205.3  798.83   214.1  802.92   222.9  807.99
#Mann= 3 , 0 , 0
       0     .06       0   133.2    .045       0   150.6     .08       0
Bank Sta=133.2,150.6
XS Rating Curve= 0 ,0
Exp/Cntr=0.3,0.1

Type RM Length L Ch R = 1 ,4469    ,269.9,264.6,258.4
XS GIS Cut Line= 4
     1586446.217      306555.393     1586461.842       306503.31
     1586490.488      306392.632     1586487.884       306297.58
#Sta/Elev= 19
       0   788.2     9.1  786.94      83  778.31     102  775.76   111.5  775.17
   121.1  775.45   125.5  776.04   130.6  776.72   140.1  778.57   149.6  780.32
   159.2  781.93   168.7  783.65   178.2     786   187.7  789.37   206.7  797.27
   216.2  801.39   225.8  805.67   235.3  810.03   263.8  823.45
#Mann= 3 , 0 , 0
       0     .06       0     102    .045       0   125.5     .08       0
Bank Sta=102,125.5
XS Rating Curve= 0 ,0
Exp/Cntr=0.3,0.1

Type RM Length L Ch R = 1 ,4204.4  ,271.6,273.8,275.5
XS GIS Cut Line= 3
     1586730.071      306607.476     1586730.071      306421.278
     1586720.957      306341.851
#Sta/Elev= 22
       0  821.21    19.6  810.57    39.2   799.8      49  794.59    58.8   789.5
    68.6  783.82    78.4     778    87.9  774.44    88.2  774.33      98  773.58
   102.9   774.1   107.8  774.63   117.6  775.94   127.4  776.62   137.2  777.01
     147  777.56     204  781.45   221.7  782.79   230.6   783.8   239.5  785.56
   248.4   788.2   266.2  794.41
#Mann= 3 , 0 , 0
       0     .08       0    87.9    .045       0   102.9     .07       0
Bank Sta=87.9,102.9
XS Rating Curve= 0 ,0
Exp/Cntr=0.3,0.1

Type RM Length L Ch R = 1 ,3930.6  ,176.6,179.8,183.3
XS GIS Cut Line= 4
     1586974.863      306619.195     1587000.905      306546.278
     1587007.415      306461.643     1587002.207      306356.174
#Sta/Elev= 22
       0  818.99     9.7  813.96    19.4  808.76    38.7  798.12    48.4  793.01
    58.1  788.24    67.8  783.58    77.4   778.6    86.9  773.39    90.8  772.02
    96.3   770.1   105.7  769.54   115.2  770.39     134  772.84   152.9  775.13
   162.3  776.49   210.3  784.62   219.9  786.44   229.5  788.48   239.1  790.72
   258.3  795.36   267.9  797.57
#Mann= 3 , 0 , 0
       0     .08       0    90.8    .045       0   115.2     .07       0
Bank Sta=90.8,115.2
XS Rating Curve= 0 ,0
Exp/Cntr=0.3,0.1

Type RM Length L Ch R = 1 ,3750.7  ,301.8,313.4,322.2
XS GIS Cut Line= 4
     1587120.969      306673.633     1587165.883      306602.341
     1587183.592      306528.309     1587230.479      306417.711
#Sta/Elev= 23
       0  816.91     9.4  812.46    37.4  798.99    46.8   794.7    56.2  790.72
    65.5  786.91    93.8   775.6   103.3  772.49   112.8  770.67   122.3  769.36
   127.3  768.92   131.8  768.53   141.4  768.51   142.3  768.63   150.9  769.74
   169.6  774.02   178.9  775.92   206.6  781.36   225.1  784.66   234.3  786.38
   243.6  789.14   252.8  793.59   280.5  810.54
#Mann= 3 , 0 , 0
       0     .07       0   127.3    .045       0   142.3     .07       0
Bank Sta=127.3,142.3
XS Rating Curve= 0 ,0
Exp/Cntr=0.3,0.1

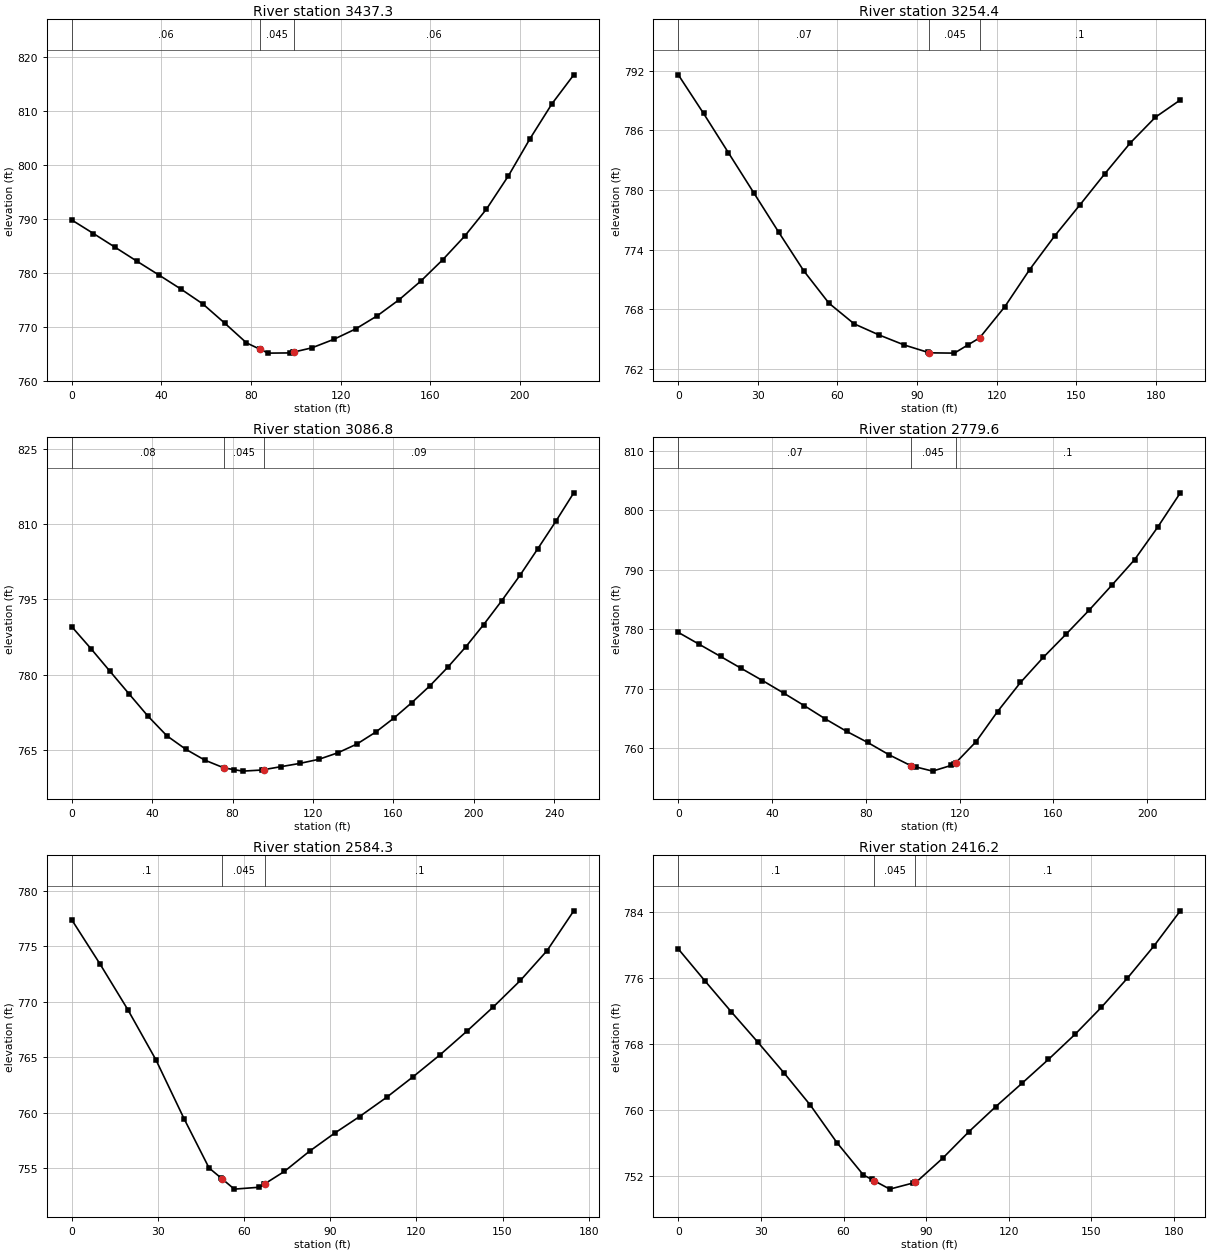
Type RM Length L Ch R = 1 ,3437.3  ,188.6,182.9,177.3
XS GIS Cut Line= 2
     1587321.217      306789.768     1587461.842      306615.289
#Sta/Elev= 28
       0  789.76     9.7  787.25    19.5  784.67    29.2   782.1      39  779.55
    48.7  776.98    58.5  774.22    68.2  770.69      78  767.01    83.9  765.85
    84.1 765.811    87.7  765.11    97.4  765.15    98.9  765.29    99.1765.3093
   107.2  766.09   116.9  767.65   126.7  769.58   136.4  772.03   146.2  775.02
   155.9  778.48   165.6   782.4   175.4  786.77   185.1  791.76   194.9  797.92
   204.6  804.84   214.4   811.3   224.1  816.64
#Mann= 3 , 0 , 0
       0     .06       0    84.1    .045       0    99.1     .06       0
Bank Sta=84.1,99.1
XS Rating Curve= 0 ,0
Exp/Cntr=0.3,0.1

Type RM Length L Ch R = 1 ,3254.4  ,154.5,167.6,179.7
XS GIS Cut Line= 2
     1587495.696      306897.841     1587575.124      306725.966
#Sta/Elev= 23
       0   791.6     9.5  787.72    18.9  783.75    28.4  779.74    37.9  775.73
    47.3  771.86    56.8   768.6    66.3  766.52    75.7   765.4    85.2  764.39
    94.1  763.65    94.7   763.6   104.1  763.57   109.1  764.38   113.6   765.1
   123.1  768.24   132.5  771.99     142   775.4   151.5  778.52   160.9  781.66
   170.4  784.73   179.9  787.33   189.3  789.07
#Mann= 3 , 0 , 0
       0     .07       0    94.7    .045       0   113.6      .1       0
Bank Sta=94.7,113.6
XS Rating Curve= 0 ,0
Exp/Cntr=0.3,0.1

Type RM Length L Ch R = 1 ,3086.8  ,295.5,307.2,316.3
XS GIS Cut Line= 3
     1587575.124      306975.966     1587701.426      306892.632
     1587787.363      306844.455
#Sta/Elev= 30
       0  789.54     9.5  785.19    18.9  780.71    28.4   776.2    37.8  771.77
    47.3  767.81    56.7  765.13    66.2  762.95    75.7  761.41    80.7  761.06
    85.1  760.76    94.6  760.98    95.7  761.06     104  761.64   113.5   762.3
   122.9  763.11   132.4  764.41   141.9  766.16   151.3  768.55   160.3  771.33
   169.2  774.41   178.2  777.76   187.1  781.46   196.1  785.54     205  789.98
     214  794.74     223  799.76   231.9  805.08   240.9  810.56   249.8  816.22
#Mann= 3 , 0 , 0
       0     .08       0    75.7    .045       0    95.7     .09       0
Bank Sta=75.7,95.7
XS Rating Curve= 0 ,0
Exp/Cntr=0.3,0.1

Type RM Length L Ch R = 1 ,2779.6  ,202,195.3,188.5
XS GIS Cut Line= 4
     1587677.988      307193.414     1587753.509      307164.768
     1587808.196      307155.653     1587878.509      307121.799
#Sta/Elev= 27
       0   779.5       9  777.48      18  775.46    26.9  773.44    35.9  771.41
    44.9  769.31    53.8  767.17    62.8  764.94    71.8  762.87    80.8     761
      90  758.91    99.2   757.1   101.5  756.87   108.5  756.18   116.5  757.15
   117.7   757.3   118.4757.5868     127  761.11   136.2  766.19     146  771.08
   155.7  775.29   165.5  779.22   175.2   783.2     185  787.44   194.7  791.73
   204.5  797.16   214.2  802.96
#Mann= 3 , 0 , 0
       0     .07       0    99.2    .045       0   118.4      .1       0
Bank Sta=99.2,118.4
XS Rating Curve= 0 ,0
Exp/Cntr=0.3,0.1

Type RM Length L Ch R = 1 ,2584.3  ,175.5,168.2,159.9
XS GIS Cut Line= 4
     1587788.665      307373.101     1587822.519       307353.57
     1587877.207      307326.226      1587929.29      307272.841
#Sta/Elev= 24
       0  777.38     9.8  773.41    19.5  769.29    29.3  764.76    39.1  759.45
    47.8  755.01    52.1  754.08    52.3754.0364    56.6   753.1    65.3  753.27
    67.1  753.56    67.3753.5928      74  754.69    82.8  756.52    91.5  758.14
   100.2  759.64   109.6  761.37   118.9  763.24   128.2   765.2   137.5  767.32
   146.8  769.53   156.2  771.91   165.5   774.6   174.8  778.19
#Mann= 3 , 0 , 0
       0      .1       0    52.3    .045       0    67.3      .1       0
Bank Sta=52.3,67.3
XS Rating Curve= 0 ,0
Exp/Cntr=0.3,0.1

Type RM Length L Ch R = 1 ,2416.2  ,176.6,176.8,176.9
XS GIS Cut Line= 2
     1587908.457      307511.122     1588034.759      307379.612
#Sta/Elev= 24
       0  779.53     9.6  775.69    19.2  771.93    28.8  768.27    38.4  764.51
      48  760.59    57.6  756.07    67.2  752.16    70.2  751.62    71.1751.4591
    76.8  750.44    85.2  751.18    86.1751.2625    86.4  751.29      96  754.18
   105.6  757.42   115.2  760.41   124.8  763.26   134.4  766.15     144  769.17
   153.6  772.45   163.1     776   172.7  779.88   182.3  784.15
#Mann= 3 , 0 , 0
       0      .1       0    71.1    .045       0    86.1      .1       0
Bank Sta=71.1,86.1
XS Rating Curve= 0 ,0
Exp/Cntr=0.3,0.1

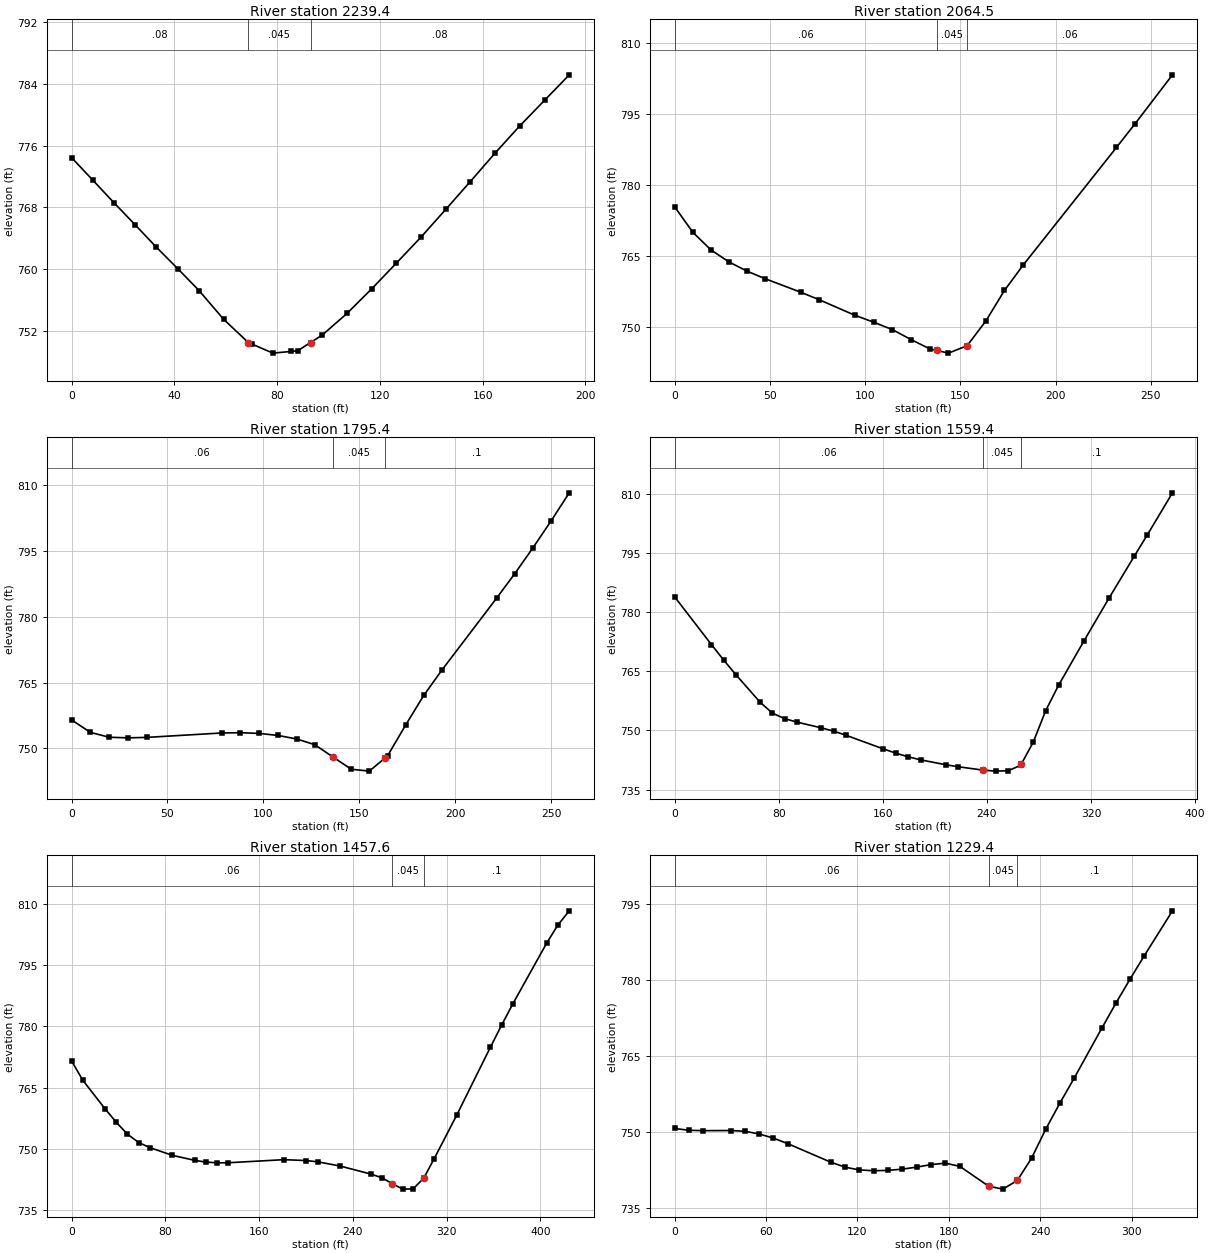
Type RM Length L Ch R = 1 ,2239.4  ,174,174.8,175.3
XS GIS Cut Line= 4
     1588028.249      307619.195     1588071.217      307594.455
     1588118.092      307546.278     1588151.946      307477.268
#Sta/Elev= 25
       0  774.44     8.3  771.51    16.5   768.6    24.8  765.72      33  762.84
    41.3  760.07    49.6  757.23    59.2   753.5    68.8  750.49    70.4  750.26
    78.4  749.12    85.4  749.34      88  749.42      93750.4877    97.6  751.47
   107.2  754.26   116.8  757.44   126.4  760.77     136  764.14   145.6  767.72
   155.2  771.34   164.8  775.01   174.4  778.53   184.1  781.86   193.7  785.16
#Mann= 3 , 0 , 0
       0     .08       0    68.8    .045       0      93     .08       0
Bank Sta=68.8,93
XS Rating Curve= 0 ,0
Exp/Cntr=0.3,0.1

Type RM Length L Ch R = 1 ,2064.5  ,265.7,269.1,272.6
XS GIS Cut Line= 3
     1588095.957      307731.174     1588189.707      307718.153
     1588309.499      307602.268
#Sta/Elev= 22
       0  775.37     9.5  770.02    18.9  766.34    28.4  763.78    37.9  761.84
    47.3  760.25    66.2  757.37    75.7  755.82    94.6  752.51   104.4  751.06
   114.3  749.48   124.1  747.38   133.9  745.43   137.6745.0931   143.7  744.53
   153.5   746.1   163.3   751.3   173.1  757.76   182.9   763.1   231.9  787.93
   241.7  792.95   261.3  803.25
#Mann= 3 , 0 , 0
       0     .06       0   137.6    .045       0   153.5     .06       0
Bank Sta=137.6,153.5
XS Rating Curve= 0 ,0
Exp/Cntr=0.3,0.1

Type RM Length L Ch R = 1 ,1795.4  ,236.5,236,233.6
XS GIS Cut Line= 3
     1588257.415      307906.955     1588374.603      307900.445
     1588490.488      307818.414
#Sta/Elev= 24
       0  756.51     9.8  753.66    19.6  752.55    29.3  752.41    39.1  752.51
    78.2  753.52      88  753.59    97.8  753.42   107.6  752.96   117.4  752.15
   126.8  750.85   136.3  748.02   145.8  745.25   155.2  744.82   163.2  747.75
   164.7   748.3   174.2  755.38   183.6  762.11   193.1  767.91   221.5  784.25
     231  789.86   240.4  795.71   249.9  801.86   259.4   808.3
#Mann= 3 , 0 , 0
       0     .06       0   136.3    .045       0   163.2      .1       0
Bank Sta=136.3,163.2
XS Rating Curve= 0 ,0
Exp/Cntr=0.3,0.1

Type RM Length L Ch R = 1 ,1559.4  ,109.5,101.8,94.6
XS GIS Cut Line= 4
     1588287.363      308143.935     1588417.571      308162.164
     1588532.155      308074.924     1588581.634      307979.872
#Sta/Elev= 30
       0   783.8    28.2  771.74    37.6  767.82      47   764.1    65.7  757.09
    75.1  754.36    84.5  752.96    93.9  752.09   112.7  750.63   122.1   749.8
   131.5  748.77   160.3  745.29   169.9  744.22   179.5  743.28   189.1  742.51
   208.3  741.28   217.9  740.77   237.1  739.91   246.7  739.66   256.3  739.76
   265.9  741.14   266.4741.4426   275.5  746.95   285.2  755.03     295   761.4
   314.5  772.64   333.9  783.57   353.4  794.24   363.2  799.52   382.6  810.22
#Mann= 3 , 0 , 0
       0     .06       0   237.1    .045       0   266.4      .1       0
Bank Sta=237.1,266.4
XS Rating Curve= 0 ,0
Exp/Cntr=0.3,0.1

Type RM Length L Ch R = 1 ,1457.6  ,232.3,228.3,224.3
XS GIS Cut Line= 4
     1588515.228      308432.997     1588556.894      308207.737
     1588599.863      308140.028     1588632.415      308029.351
#Sta/Elev= 30
       0  771.58     9.6   766.8    28.6   759.8    38.2  756.47    47.7  753.58
    57.3  751.53    66.8  750.28    85.9   748.4     105  747.16   114.5  746.74
   124.1  746.55   133.6  746.57   181.4  747.33   200.4   747.1     210   746.8
   229.1  745.77   255.8  743.76   264.7  742.89   273.6  741.45   282.5   740.1
   291.4  740.16   300.4  742.77   309.3  747.53   328.5  758.19   357.3  774.89
     367  780.39   376.6  785.62   405.4  800.48     415  804.92   424.6  808.37
#Mann= 3 , 0 , 0
       0     .06       0   273.6    .045       0   300.4      .1       0
Bank Sta=273.6,300.4
XS Rating Curve= 0 ,0
Exp/Cntr=0.3,0.1

Type RM Length L Ch R = 1 ,1229.4  ,126.3,127.9,129.3
XS GIS Cut Line= 4
     1588694.481      308438.639     1588737.204       308390.13
     1588803.856      308223.796     1588858.544      308161.296
#Sta/Elev= 30
       0   750.6     9.2  750.25    18.5  750.17    36.9   750.2    46.2  750.04
    55.4  749.52    64.6  748.72    74.1  747.62   102.4  743.96   111.8  742.97
   121.2  742.42   130.7  742.26   140.1  742.33   149.5  742.58     159  742.98
   168.4  743.48   177.8  743.75   187.2  743.13   206.1  739.22   215.5  738.63
     225  740.34   234.4  744.77   243.8  750.55   253.1  755.68   262.3  760.52
   280.7  770.51     290  775.47   299.2  780.17   308.4  784.71   326.9  793.57
#Mann= 3 , 0 , 0
       0     .06       0   206.1    .045       0     225      .1       0
Bank Sta=206.1,225
XS Rating Curve= 0 ,0
Exp/Cntr=0.3,0.1

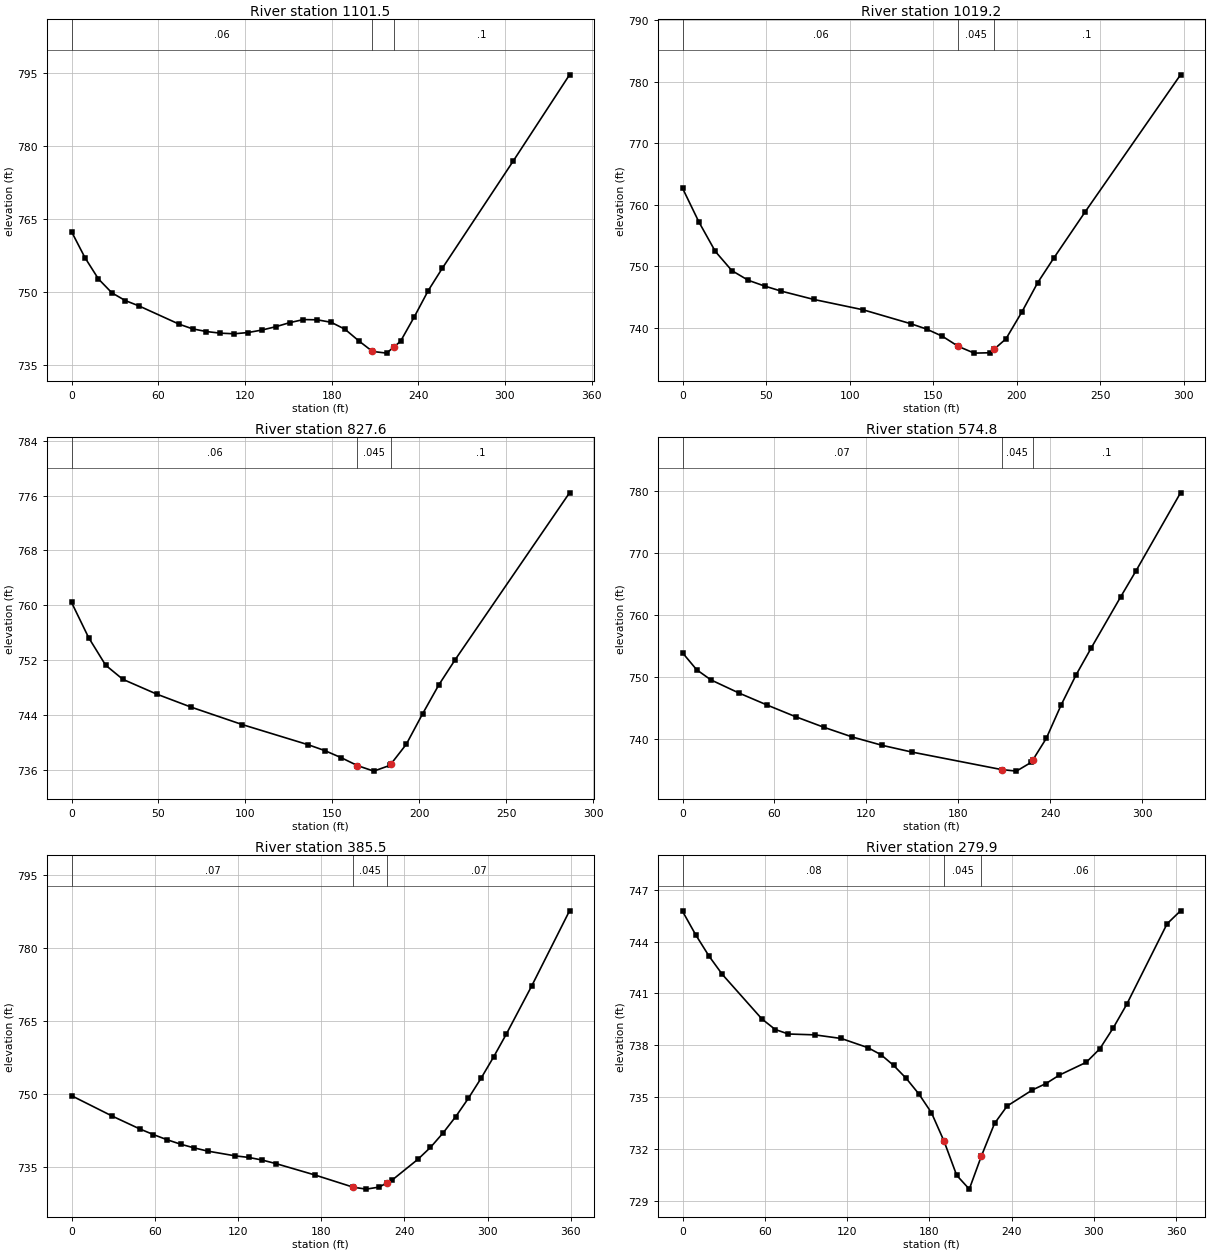
Type RM Length L Ch R = 1 ,1101.5  ,82.7,82.3,81.7
XS GIS Cut Line= 4
     1588806.894      308492.893     1588852.467       308422.58
      1588922.78      308275.445     1588939.707      308179.091
#Sta/Elev= 29
       0  762.34     9.3     757    18.6  752.64    27.9  749.79    37.2   748.2
    46.6  747.11    74.5  743.35    83.8  742.39    93.4  741.84     103  741.51
   112.6  741.38   122.2  741.64   131.8  742.15   141.3  742.83   150.9  743.66
   160.5   744.3   170.1  744.25   179.7  743.74   189.3  742.31   198.9  739.91
   208.3  737.76   218.1  737.41   223.3  738.72   227.7  739.83   237.3  744.89
   246.9  750.25   256.6  754.82   305.6  776.79   344.7  794.55
#Mann= 3 , 0 , 0
       0     .06       0   208.3    .045       0   223.3      .1       0
Bank Sta=208.3,223.3
XS Rating Curve= 0 ,0
Exp/Cntr=0.3,0.1

Type RM Length L Ch R = 1 ,1019.2  ,190.5,191.6,191.3
XS GIS Cut Line= 3
     1588950.124      308517.632     1588951.426       308409.56
     1589029.551      308236.382
#Sta/Elev= 22
       0  762.67     9.8  757.18    19.6  752.41    29.5  749.29    39.3  747.72
    49.1  746.78      59  745.96    78.6   744.6   108.1  742.92   136.6  740.66
   146.1  739.79   155.6  738.61   165.1  736.97   174.6  735.88   184.1  735.94
   186.4 736.487   193.6   738.2   203.1  742.55   212.6  747.33   222.1  751.27
   241.1  758.87   298.1   781.1
#Mann= 3 , 0 , 0
       0     .06       0   165.1    .045       0   186.4      .1       0
Bank Sta=165.1,186.4
XS Rating Curve= 0 ,0
Exp/Cntr=0.3,0.1

Type RM Length L Ch R = 1 ,827.6   ,246.9,252.8,259.4
XS GIS Cut Line= 4
      1589079.03       308547.58     1589135.019      308455.132
      1589172.78      308379.612     1589200.124      308289.768
#Sta/Elev= 19
       0   760.4     9.8  755.28    19.6  751.25    29.5  749.19    49.1  747.02
    68.8  745.13    98.3  742.58   136.2  739.64   145.6   738.8     155  737.77
   164.4  736.61   173.8   735.8   183.1  736.64   183.8  736.87   192.5  739.71
   201.9  744.16   211.3  748.41   220.7  752.08   286.4  776.39
#Mann= 3 , 0 , 0
       0     .06       0   164.4    .045       0   183.8      .1       0
Bank Sta=164.4,183.8
XS Rating Curve= 0 ,0
Exp/Cntr=0.3,0.1

Type RM Length L Ch R = 1 ,574.8   ,192.8,189.2,185.2
XS GIS Cut Line= 3
     1589224.863      308646.539     1589317.311      308585.341
     1589457.936      308423.882
#Sta/Elev= 21
       0  753.96     9.2  751.24    18.5   749.6      37  747.46    55.4  745.52
    73.9  743.65    92.4  741.94   110.9  740.38   130.3  739.04   149.8  737.95
   208.2  735.13   217.9  734.88   227.7  736.32   228.4736.5978   237.4  740.17
   247.1  745.56   256.8  750.39   266.6   754.7     286  763.02   295.8  767.13
     325  779.78
#Mann= 3 , 0 , 0
       0     .07       0   208.2    .045       0   228.4      .1       0
Bank Sta=208.2,228.4
XS Rating Curve= 0 ,0
Exp/Cntr=0.3,0.1

Type RM Length L Ch R = 1 ,385.5   ,103.1,105.7,108.2
XS GIS Cut Line= 4
     1589383.717      308771.539     1589499.603      308680.393
     1589552.988      308593.153     1589569.915       308485.08
#Sta/Elev= 28
       0  749.67    29.5  745.46    49.1  742.86      59  741.69    68.8  740.64
    78.6  739.72    88.5  738.95    98.3  738.29     118  737.32   127.8     737
   137.6  736.45   147.4  735.73   175.3  733.41   203.2  730.88   212.5  730.49
   221.8  730.91   227.6731.7971   231.1  732.33   249.7   736.6   258.8  739.05
   267.9  742.02   277.1   745.4   286.2  749.15   295.3  753.25   304.4  757.65
   313.5  762.31   331.8  772.19   359.1  787.63
#Mann= 3 , 0 , 0
       0     .07       0   203.2    .045       0   227.6     .07       0
Bank Sta=203.2,227.6
XS Rating Curve= 0 ,0
Exp/Cntr=0.3,0.1

Type RM Length L Ch R = 1 ,279.9   ,67.7,67.8,69
XS GIS Cut Line= 4
     1589469.655      308819.716     1589584.238      308731.174
     1589651.946      308643.935     1589692.311      308543.674
#Sta/Elev= 30
       0  745.75     9.6  744.39    19.3  743.16      29   742.1    57.9  739.52
    67.6  738.91    77.2  738.65    96.5   738.6   115.8  738.39   135.2  737.86
   144.8  737.45     154  736.83   163.2  736.08   172.4  735.18   181.6  734.09
   190.8  732.44     200  730.47   209.2  729.67   217.9731.5613   227.6  733.47
   236.8  734.48   255.2  735.41   265.1  735.78   274.9  736.27   294.5  737.01
   304.4  737.79   314.2     739     324  740.36   353.5  745.03   363.3  745.78
#Mann= 3 , 0 , 0
       0     .08       0   190.8    .045       0   217.9     .06       0
Bank Sta=190.8,217.9
XS Rating Curve= 0 ,0
Exp/Cntr=0.3,0.1

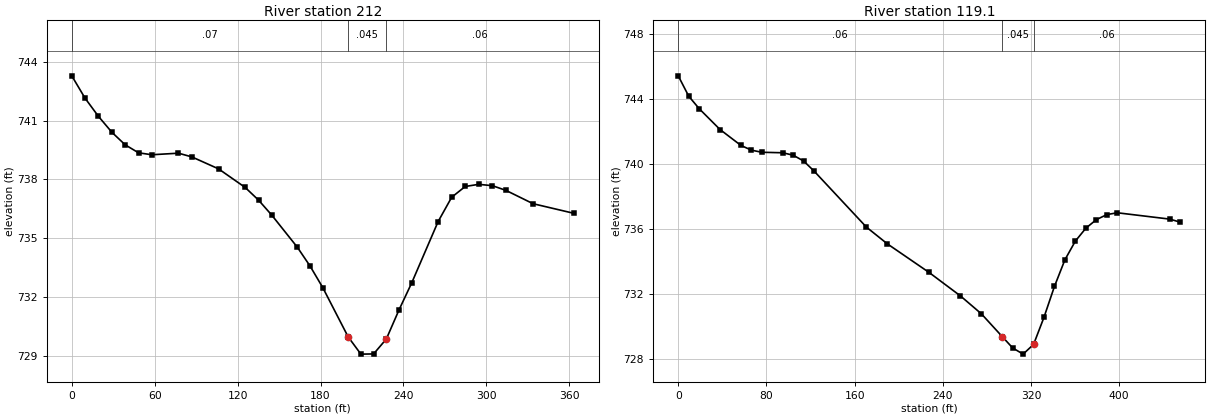
Type RM Length L Ch R = 1 ,212     ,105.2,92.9,79.5
XS GIS Cut Line= 4
     1589526.946       308853.57      1589641.53      308765.028
     1589709.238      308677.789     1589749.603      308577.528
#Sta/Elev= 30
       0  743.29     9.6  742.15    19.3  741.22      29  740.41    38.6  739.77
    48.3  739.36    57.9  739.26    77.2  739.34    86.9  739.15   106.2  738.54
   125.5  737.59   135.2  736.94   144.8  736.17   163.2  734.54   172.4  733.58
   181.6  732.48     200  729.96   209.2  729.08   218.4  729.09   227.6  729.85
   236.8  731.34     246  732.72   265.1  735.85   274.9  737.09   284.7  737.64
   294.5  737.75   304.4  737.68   314.2  737.44   333.8  736.76   363.3  736.27
#Mann= 3 , 0 , 0
       0     .07       0     200    .045       0   227.6     .06       0
Bank Sta=200,227.6
XS Rating Curve= 0 ,0
Exp/Cntr=0.3,0.1

Type RM Length L Ch R = 1 ,119.1   ,132.6,119.1,105.6
XS GIS Cut Line= 4
     1589564.707      308935.601      1589766.53      308778.049
     1589776.946      308693.414     1589762.624      308580.132
#Sta/Elev= 30
       0  745.42     9.5  744.17      19   743.4    37.9  742.12    56.9  741.14
    66.4  740.85    75.9  740.72    94.8  740.69   104.3  740.54   113.8  740.18
   123.3  739.56   170.7  736.12   189.7  735.09   227.6  733.33     256  731.89
     275  730.79   293.9  729.39   303.4  728.69   312.9  728.31   322.4  728.91
   331.8  730.57   341.3  732.47   350.8  734.11   360.3  735.26   369.9  736.06
   379.4  736.58   388.9  736.89   398.4     737     446  736.61   455.5  736.42
#Mann= 3 , 0 , 0
       0     .06       0   293.9    .045       0   322.4     .06       0
Bank Sta=293.9,322.4
XS Rating Curve= 0 ,0
Exp/Cntr=0.3,0.1

Chan Stop Cuts=-1
Use User Specified Reach Order=0
Composite Channel Slope=5

--- SHORTRN.g02 (geometry) ---

Geom Title=USGS 10m DEM_old
Program Version=4.10

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
River Reach=SHORTRN         ,Main
Reach XY= 30
     1585440.875      305918.778     1585597.125      306059.295
     1585647.907      306169.972     1585960.407      306360.076
        1586144.      306442.107     1586235.146      306418.669
     1586352.334      306422.576     1586500.771      306446.013
     1586707.802      306511.117     1586819.782      306505.909
     1586882.281      306530.649     1587058.063      306521.534
     1587170.042      306554.086     1587301.552      306535.857
     1587347.125      306613.982      1587362.75      306702.524
     1587611.448      306858.774     1587688.246      306982.838
     1587778.325      307014.104     1587794.496      307223.984
     1587867.152      307380.371     1588359.278      307801.916
     1588475.598       308023.27     1588579.391      308152.109
     1588962.577      308339.242     1589098.861      308388.721
     1589249.903      308406.083     1589308.063      308432.124
     1589686.535      308716.847      1589890.05       308702.64