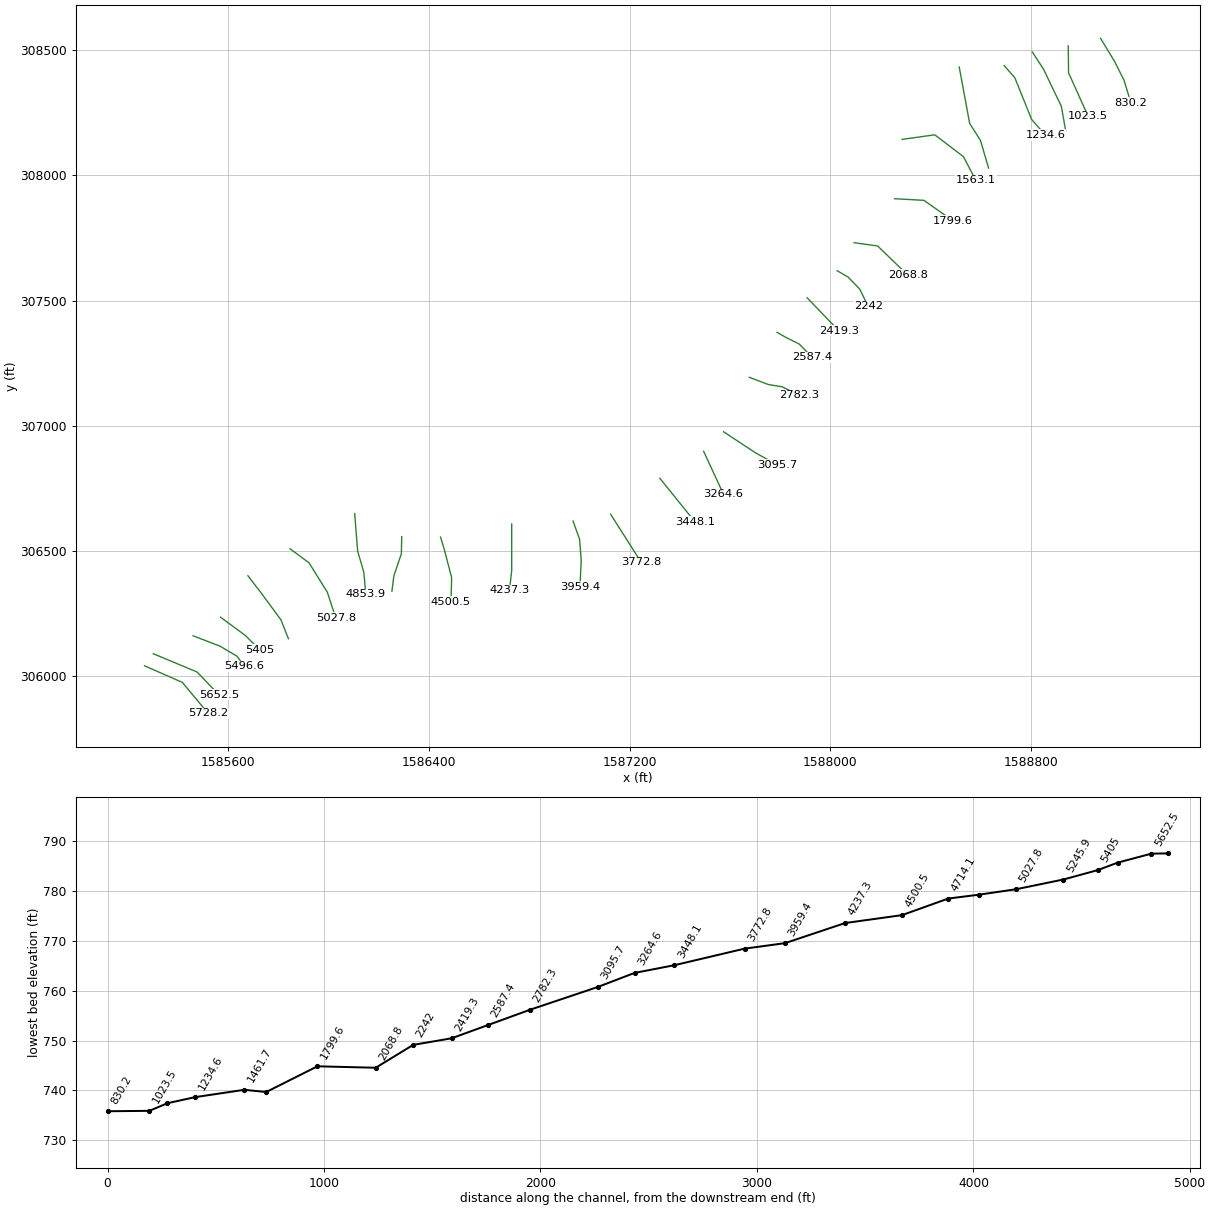
HEC-RAS study SHORTRN.prj: SHORTRN

--- SHORTRN.g02 (geometry) --- (continued)

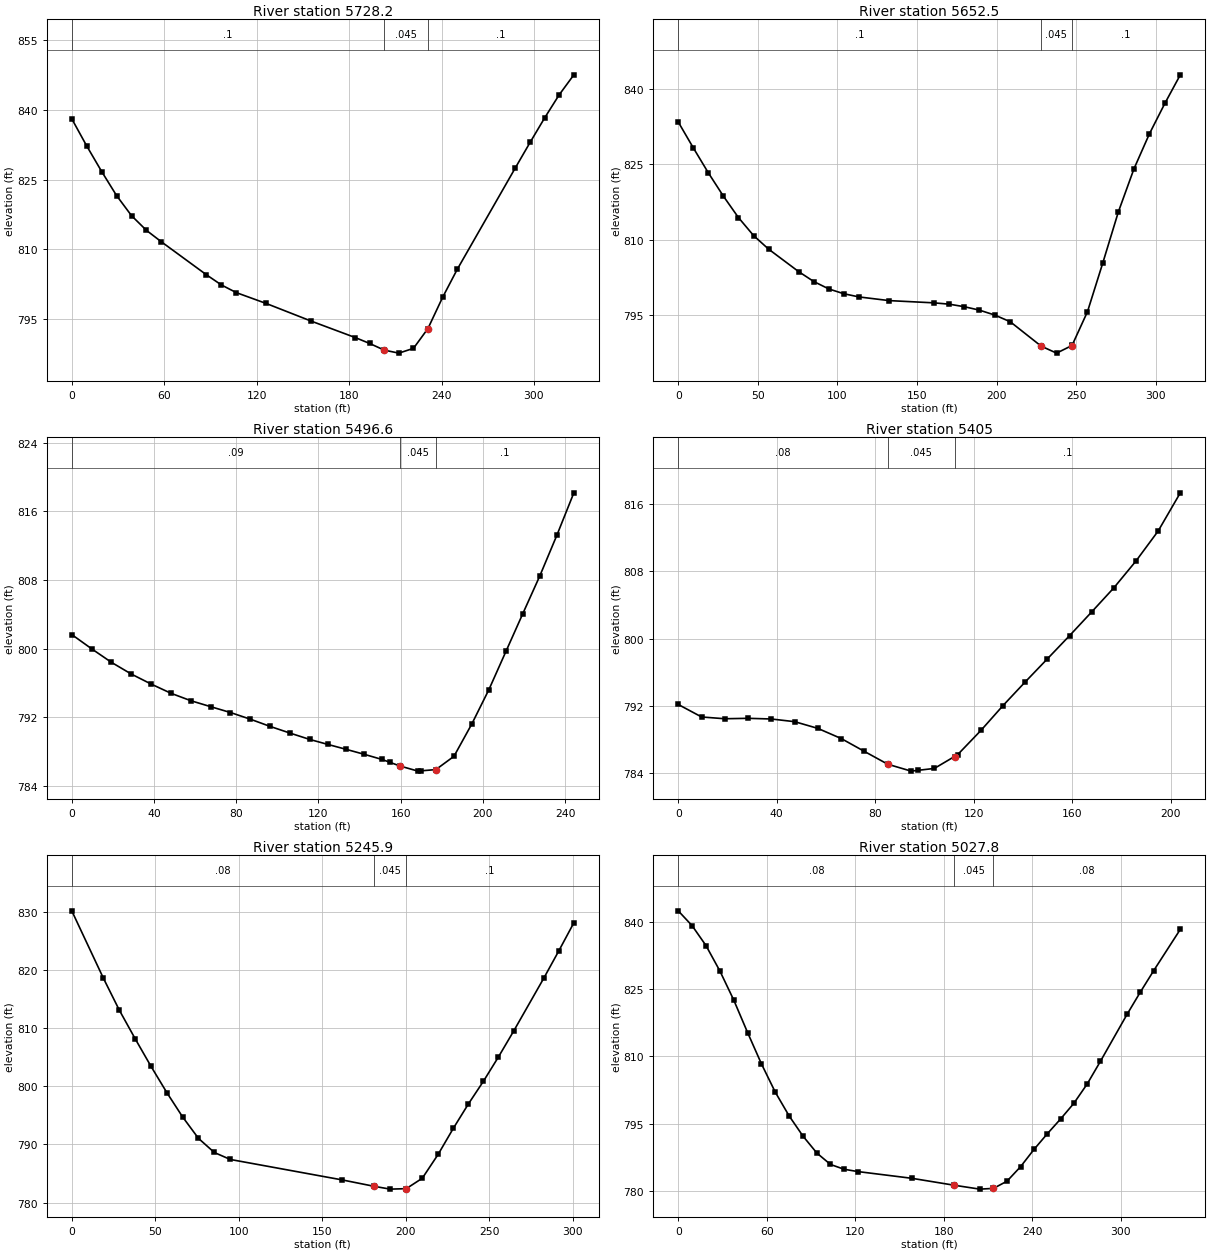
Type RM Length L Ch R = 1 ,5728.2  ,74.1,75.7,77.3
XS GIS Cut Line= 3
     1585265.228       306041.07     1585416.269      305974.664
     1585519.134      305850.966
#Sta/Elev= 25
       0   838.1     9.7  832.24    19.4  826.73    29.1  821.53    38.8   817.2
    48.5  814.03    58.2  811.56    87.4  804.46    97.1  802.27   106.8  800.61
   126.2  798.27   155.3  794.48   183.9  790.93   193.4  789.64   202.8  788.21
   212.3  787.56   221.8  788.59   231.2  792.87   240.7  799.58   250.2  805.62
     288  827.56   297.5  833.01     307  838.32   316.4  843.28   325.9  847.58
#Mann= 3 , 0 , 0
       0      .1       0   202.8    .045       0   231.2      .1       0
Bank Sta=202.8,231.2
XS Rating Curve= 0 ,0
Exp/Cntr=0.3,0.1

Type RM Length L Ch R = 1 ,5652.5  ,149.4,155.9,162.3
XS GIS Cut Line= 3
     1585300.384      306089.247     1585474.863       306016.33
     1585562.103      305925.185
#Sta/Elev= 30
       0  833.41     9.5  828.25    18.9  823.31    28.4  818.66    37.8  814.43
    47.3  810.86    56.7  808.17    75.6   803.7    85.1  801.73    94.6  800.25
     104   799.3   113.5  798.67   132.4  797.94   160.7  797.49   170.2  797.23
   179.6  796.73   189.1  796.05   198.8  795.07   208.5  793.74   227.9   788.9
   237.6  787.51     247  788.98   247.3  789.03     257  795.74   266.7   805.5
   276.4  815.56   286.2  824.11   295.9  831.06   305.6   837.1   315.3  842.77
#Mann= 3 , 0 , 0
       0      .1       0   227.9    .045       0     247      .1       0
Bank Sta=227.9,247
XS Rating Curve= 0 ,0
Exp/Cntr=0.3,0.1

Type RM Length L Ch R = 1 ,5496.6  ,93.4,91.6,89
XS GIS Cut Line= 4
     1585459.238      306160.862     1585567.311      306119.195
     1585635.019       306078.83     1585663.665      306038.466
#Sta/Elev= 30
       0  801.63     9.6  799.98    19.3  798.39      29  797.02    38.6  795.86
    48.3  794.78    57.9  793.92    67.6  793.22    77.2  792.54    86.9  791.76
    96.5  790.92   106.2  790.14   115.8   789.4   124.6  788.82   133.3  788.26
   142.1  787.68   150.9  787.07   154.7  786.74   159.6  786.31   168.4  785.71
   169.7  785.74   177.1  785.89   185.9  787.44   194.6  791.22   202.9  795.22
   211.2  799.68   219.4  804.08   227.6  808.44   235.9  813.18   244.2  818.15
#Mann= 3 , 0 , 0
       0     .09       0   159.6    .045       0   177.1      .1       0
Bank Sta=159.6,177.1
XS Rating Curve= 0 ,0
Exp/Cntr=0.3,0.1

Type RM Length L Ch R = 1 ,5405    ,166.4,159.2,152.9
XS GIS Cut Line= 3
     1585568.613       306235.08     1585667.571      306162.164
     1585724.863      306104.872
#Sta/Elev= 25
       0  792.15     9.5  790.66    18.9  790.45    28.4   790.5    37.8  790.42
    47.3   790.1    56.7   789.3    66.2  788.09    75.6  786.56    85.1  785.03
    94.6  784.21    97.2   784.3     104  784.53   112.2  785.95   113.5  786.18
   122.9  789.05   131.9  792.02   140.9  794.83   149.9  797.58   158.9  800.34
   167.9  803.17   176.9  806.04   185.9  809.24   194.9  812.81   203.9  817.36
#Mann= 3 , 0 , 0
       0     .08       0    85.1    .045       0   112.2      .1       0
Bank Sta=85.1,112.2
XS Rating Curve= 0 ,0
Exp/Cntr=0.3,0.1

Type RM Length L Ch R = 1 ,5245.9  ,219.8,218.1,216.4
XS GIS Cut Line= 4
     1585677.988      306400.445     1585730.071      306332.737
     1585809.499      306224.664     1585839.446      306149.143
#Sta/Elev= 24
       0  830.18      19  818.56    28.5  813.09      38  808.17    47.5  803.42
      57   798.9    66.4  794.74    75.9  791.05    85.4  788.62      95  787.42
   162.1   783.9   181.2   782.8   190.8  782.32   200.4   782.4     210  784.19
   219.5   788.3   228.6  792.78   237.6  796.96   246.6  800.86   255.6  805.04
   264.7  809.48   282.7  818.55   291.8   823.3   300.8  828.12
#Mann= 3 , 0 , 0
       0     .08       0   181.2    .045       0   200.4      .1       0
Bank Sta=181.2,200.4
XS Rating Curve= 0 ,0
Exp/Cntr=0.3,0.1

Type RM Length L Ch R = 1 ,5027.8  ,180,173.9,167.7
XS GIS Cut Line= 4
     1585845.957      306508.518     1585921.478      306452.528
     1585994.394      306335.341     1586028.249      306232.476
#Sta/Elev= 30
       0  842.41     9.4   839.1    18.8  834.67    28.2  829.02    37.6  822.54
      47  815.28    56.4  808.29    65.8  801.97    75.2  796.67    84.6  792.17
      94   788.4   103.2  785.87   112.4   784.8   121.6  784.29   158.4  782.78
   187.2  781.23   204.4  780.37   213.6  780.53   222.8  782.13     232  785.36
   241.1  789.21   250.1  792.69   259.1  795.99   268.1  799.48   277.2  803.82
   286.2  808.89   304.2  819.33   313.2  824.29   322.3   829.1   340.3  838.28
#Mann= 3 , 0 , 0
       0     .08       0   187.2    .045       0   213.6     .08       0
Bank Sta=187.2,213.6
XS Rating Curve= 0 ,0
Exp/Cntr=0.3,0.1

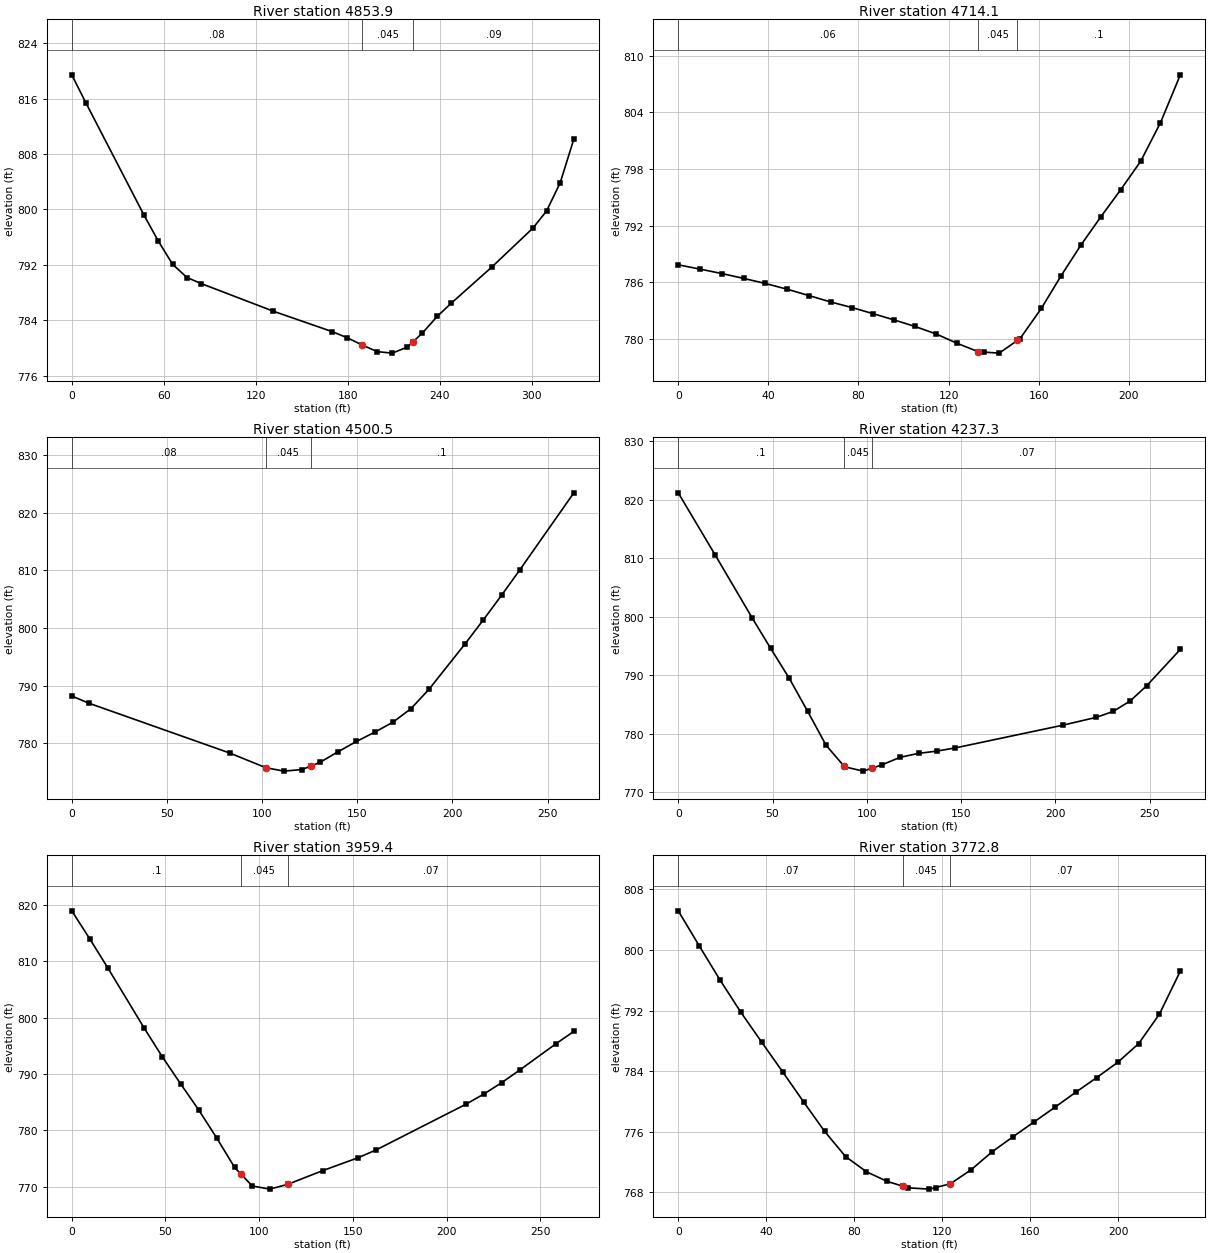
Type RM Length L Ch R = 1 ,4853.9  ,154.3,139.8,126.6
XS GIS Cut Line= 4
     1586103.769      306649.143     1586115.488      306499.403
     1586140.228      306414.768      1586148.04      306326.226
#Sta/Elev= 23
       0  819.43     9.4   815.3    46.9  799.26    56.3  795.48    65.7  792.09
    75.1  790.17    84.5  789.29   131.4  785.31   169.8  782.36   179.6  781.48
   189.4  780.42   199.2  779.47     209  779.26   218.8  780.14   222.4  780.89
   228.6  782.17   238.4   784.6   247.3  786.45   273.9   791.7   300.6   797.3
   309.5  799.77   318.4  803.85   327.3  810.16
#Mann= 3 , 0 , 0
       0     .08       0   189.4    .045       0   222.4     .09       0
Bank Sta=189.4,222.4
XS Rating Curve= 0 ,0
Exp/Cntr=0.3,0.1

Type RM Length L Ch R = 1 ,4714.1  ,199.8,213.6,225.5
XS GIS Cut Line= 4
     1586291.269      306556.695     1586289.967      306488.987
     1586260.019      306400.445     1586252.207      306339.247
#Sta/Elev= 27
       0  787.86     9.7   787.4    19.4  786.93      29  786.42    38.7  785.88
    48.4  785.27      58   784.6    67.7  783.92    77.1  783.33    86.4  782.69
    95.8  782.02   105.1  781.33   114.5  780.53   123.8  779.54   133.2  778.65
   135.6  778.61   142.5   778.5   150.6  779.85   151.8  780.05   161.2  783.24
     170  786.71   178.8  789.96   187.6  792.94   196.4   795.8   205.3  798.83
   214.1  802.92   222.9  807.99
#Mann= 3 , 0 , 0
       0     .06       0   133.2    .045       0   150.6      .1       0
Bank Sta=133.2,150.6
XS Rating Curve= 0 ,0
Exp/Cntr=0.3,0.1

Type RM Length L Ch R = 1 ,4500.5  ,269,263.2,257.6
XS GIS Cut Line= 4
     1586446.217      306555.393     1586461.842       306503.31
     1586490.488      306392.632     1586487.884       306297.58
#Sta/Elev= 19
       0   788.2     9.1  786.94      83  778.31     102  775.76   111.5  775.17
   121.1  775.45   125.5  776.04   130.6  776.72   140.1  778.57   149.6  780.32
   159.2  781.93   168.7  783.65   178.2     786   187.7  789.37   206.7  797.27
   216.2  801.39   225.8  805.67   235.3  810.03   263.8  823.45
#Mann= 3 , 0 , 0
       0     .08       0     102    .045       0   125.5      .1       0
Bank Sta=102,125.5
XS Rating Curve= 0 ,0
Exp/Cntr=0.3,0.1

Type RM Length L Ch R = 1 ,4237.3  ,275.1,277.9,279.8
XS GIS Cut Line= 3
     1586730.071      306607.476     1586730.071      306421.278
     1586720.957      306341.851
#Sta/Elev= 22
       0  821.21    19.6  810.57    39.2   799.8      49  794.59    58.8   789.5
    68.6  783.82    78.4     778    87.9  774.44    88.2  774.33      98  773.58
   102.9   774.1   107.8  774.63   117.6  775.94   127.4  776.62   137.2  777.01
     147  777.56     204  781.45   221.7  782.79   230.6   783.8   239.5  785.56
   248.4   788.2   266.2  794.41
#Mann= 3 , 0 , 0
       0      .1       0    87.9    .045       0   102.9     .07       0
Bank Sta=87.9,102.9
XS Rating Curve= 0 ,0
Exp/Cntr=0.3,0.1

Type RM Length L Ch R = 1 ,3959.4  ,175,186.5,199.3
XS GIS Cut Line= 4
     1586974.863      306619.195     1587000.905      306546.278
     1587007.415      306461.643     1587002.207      306356.174
#Sta/Elev= 22
       0  818.99     9.7  813.96    19.4  808.76    38.7  798.12    48.4  793.01
    58.1  788.24    67.8  783.58    77.4   778.6    86.9  773.39    90.2  772.24
    96.3   770.1   105.7  769.54   115.2  770.39     134  772.84   152.9  775.13
   162.3  776.49   210.3  784.62   219.9  786.44   229.5  788.48   239.1  790.72
   258.3  795.36   267.9  797.57
#Mann= 3 , 0 , 0
       0      .1       0    90.2    .045       0   115.2     .07       0
Bank Sta=90.2,115.2
XS Rating Curve= 0 ,0
Exp/Cntr=0.3,0.1

Type RM Length L Ch R = 1 ,3772.8  ,322.5,324.7,326.1
XS GIS Cut Line= 2
     1587124.603      306646.539     1587246.999       306453.83
#Sta/Elev= 27
       0  805.18     9.5  800.58      19  796.05    28.5  791.78      38  787.82
    47.6  783.87    57.1  779.92    66.6  776.05    76.1  772.74    85.6  770.73
    95.1  769.45     102  768.84   104.6  768.61   114.2  768.44     117  768.65
   123.7  769.14   133.2     771   142.7  773.36   152.2  775.35   161.7  777.29
   171.2  779.23   180.7  781.22   190.2  783.15   199.8  785.17   209.3  787.63
   218.8  791.54   228.3  797.22
#Mann= 3 , 0 , 0
       0     .07       0     102    .045       0   123.7     .07       0
Bank Sta=102,123.7
XS Rating Curve= 0 ,0
Exp/Cntr=0.3,0.1

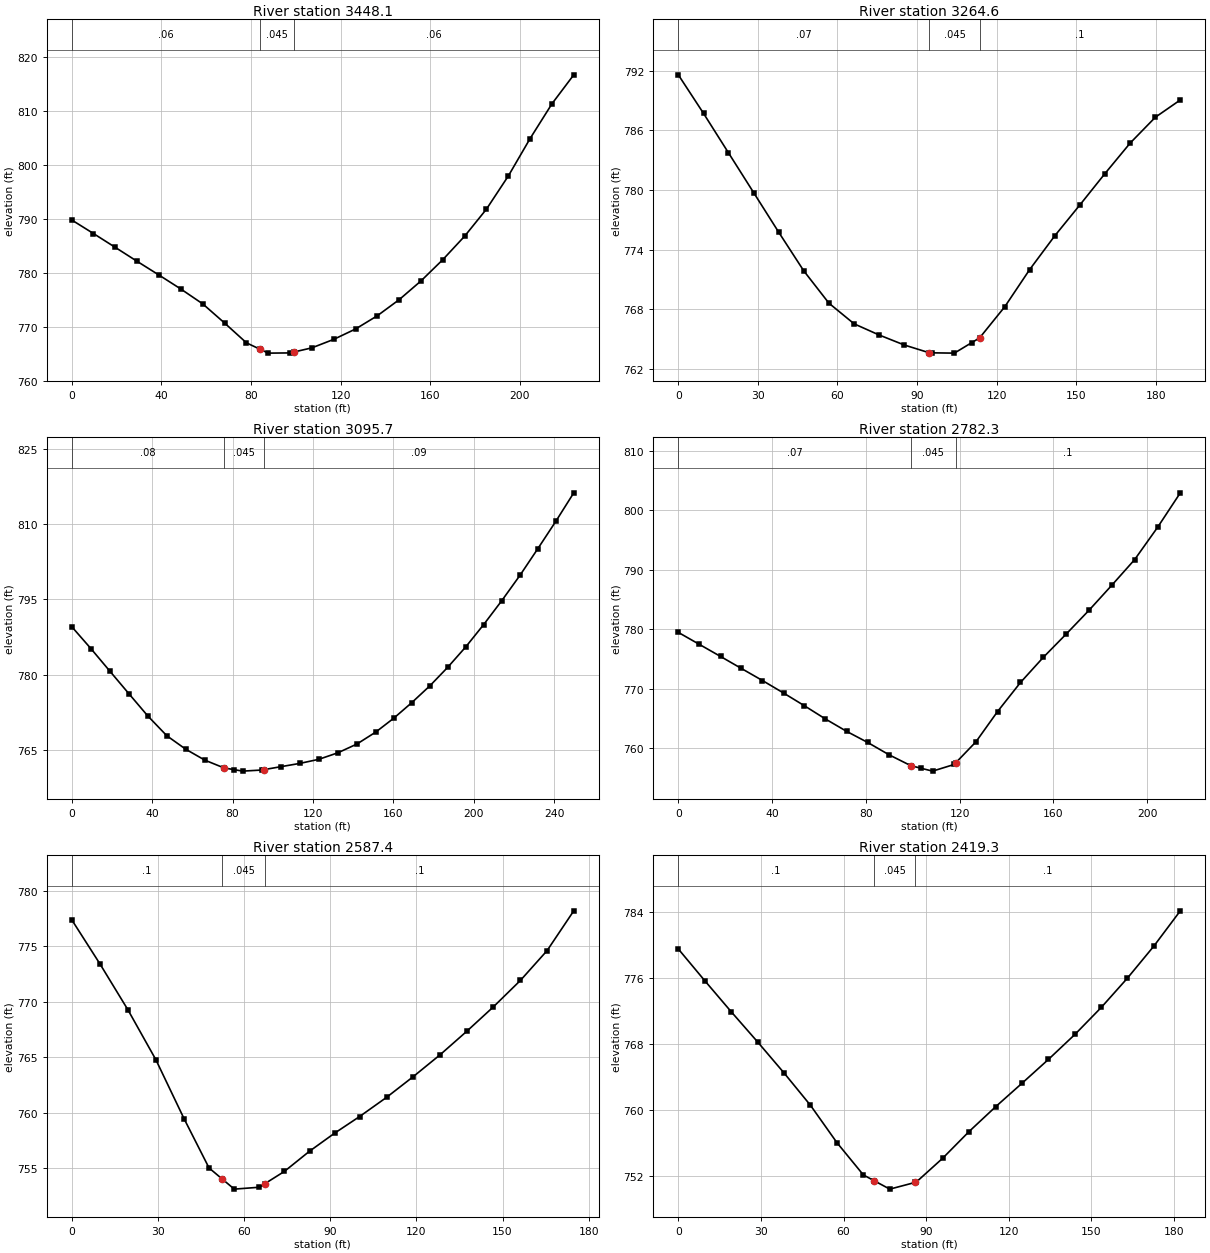
Type RM Length L Ch R = 1 ,3448.1  ,189.3,183.6,177.8
XS GIS Cut Line= 2
     1587321.217      306789.768     1587461.842      306615.289
#Sta/Elev= 26
       0  789.76     9.7  787.25    19.5  784.67    29.2   782.1      39  779.55
    48.7  776.98    58.5  774.22    68.2  770.69      78  767.01    84.1  765.82
    87.7  765.11    97.4  765.15    99.1  765.31   107.2  766.09   116.9  767.65
   126.7  769.58   136.4  772.03   146.2  775.02   155.9  778.48   165.6   782.4
   175.4  786.77   185.1  791.76   194.9  797.92   204.6  804.84   214.4   811.3
   224.1  816.64
#Mann= 3 , 0 , 0
       0     .06       0    84.1    .045       0    99.1     .06       0
Bank Sta=84.1,99.1
XS Rating Curve= 0 ,0
Exp/Cntr=0.3,0.1

Type RM Length L Ch R = 1 ,3264.6  ,156,168.9,181.4
XS GIS Cut Line= 2
     1587495.696      306897.841     1587575.124      306725.966
#Sta/Elev= 23
       0   791.6     9.5  787.72    18.9  783.75    28.4  779.74    37.9  775.73
    47.3  771.86    56.8   768.6    66.3  766.52    75.7   765.4    85.2  764.39
    94.7   763.6    95.6   763.6   104.1  763.57   110.6  764.62   113.6   765.1
   123.1  768.24   132.5  771.99     142   775.4   151.5  778.52   160.9  781.66
   170.4  784.73   179.9  787.33   189.3  789.07
#Mann= 3 , 0 , 0
       0     .07       0    94.7    .045       0   113.6      .1       0
Bank Sta=94.7,113.6
XS Rating Curve= 0 ,0
Exp/Cntr=0.3,0.1

Type RM Length L Ch R = 1 ,3095.7  ,302.2,313.4,323
XS GIS Cut Line= 3
     1587575.124      306975.966     1587701.426      306892.632
     1587787.363      306844.455
#Sta/Elev= 30
       0  789.54     9.5  785.19    18.9  780.71    28.4   776.2    37.8  771.77
    47.3  767.81    56.7  765.13    66.2  762.95    75.7  761.41    80.7  761.06
    85.1  760.76    94.6  760.98    95.7  761.06     104  761.64   113.5   762.3
   122.9  763.11   132.4  764.41   141.9  766.16   151.3  768.55   160.3  771.33
   169.2  774.41   178.2  777.76   187.1  781.46   196.1  785.54     205  789.98
     214  794.74     223  799.76   231.9  805.08   240.9  810.56   249.8  816.22
#Mann= 3 , 0 , 0
       0     .08       0    75.7    .045       0    95.7     .09       0
Bank Sta=75.7,95.7
XS Rating Curve= 0 ,0
Exp/Cntr=0.3,0.1

Type RM Length L Ch R = 1 ,2782.3  ,201.7,195,188.2
XS GIS Cut Line= 4
     1587677.988      307193.414     1587753.509      307164.768
     1587808.196      307155.653     1587878.509      307121.799
#Sta/Elev= 26
       0   779.5       9  777.48      18  775.46    26.9  773.44    35.9  771.41
    44.9  769.31    53.8  767.17    62.8  764.94    71.8  762.87    80.8     761
      90  758.91    99.2   757.1   103.4  756.68   108.5  756.18   117.7   757.3
   118.4  757.59     127  761.11   136.2  766.19     146  771.08   155.7  775.29
   165.5  779.22   175.2   783.2     185  787.44   194.7  791.73   204.5  797.16
   214.2  802.96
#Mann= 3 , 0 , 0
       0     .07       0    99.2    .045       0   118.4      .1       0
Bank Sta=99.2,118.4
XS Rating Curve= 0 ,0
Exp/Cntr=0.3,0.1

Type RM Length L Ch R = 1 ,2587.4  ,175.5,168.1,159.8
XS GIS Cut Line= 4
     1587788.665      307373.101     1587822.519       307353.57
     1587877.207      307326.226      1587929.29      307272.841
#Sta/Elev= 22
       0  777.38     9.8  773.41    19.5  769.29    29.3  764.76    39.1  759.45
    47.8  755.01    52.3  754.03    56.6   753.1    65.3  753.27    67.3   753.6
      74  754.69    82.8  756.52    91.5  758.14   100.2  759.64   109.6  761.37
   118.9  763.24   128.2   765.2   137.5  767.32   146.8  769.53   156.2  771.91
   165.5   774.6   174.8  778.19
#Mann= 3 , 0 , 0
       0      .1       0    52.3    .045       0    67.3      .1       0
Bank Sta=52.3,67.3
XS Rating Curve= 0 ,0
Exp/Cntr=0.3,0.1

Type RM Length L Ch R = 1 ,2419.3  ,176.8,177.3,177.2
XS GIS Cut Line= 2
     1587908.457      307511.122     1588034.759      307379.612
#Sta/Elev= 22
       0  779.53     9.6  775.69    19.2  771.93    28.8  768.27    38.4  764.51
      48  760.59    57.6  756.07    67.2  752.16    71.1  751.46    76.8  750.44
    86.1  751.26    86.4  751.29      96  754.18   105.6  757.42   115.2  760.41
   124.8  763.26   134.4  766.15     144  769.17   153.6  772.45   163.1     776
   172.7  779.88   182.3  784.15
#Mann= 3 , 0 , 0
       0      .1       0    71.1    .045       0    86.1      .1       0
Bank Sta=71.1,86.1
XS Rating Curve= 0 ,0
Exp/Cntr=0.3,0.1

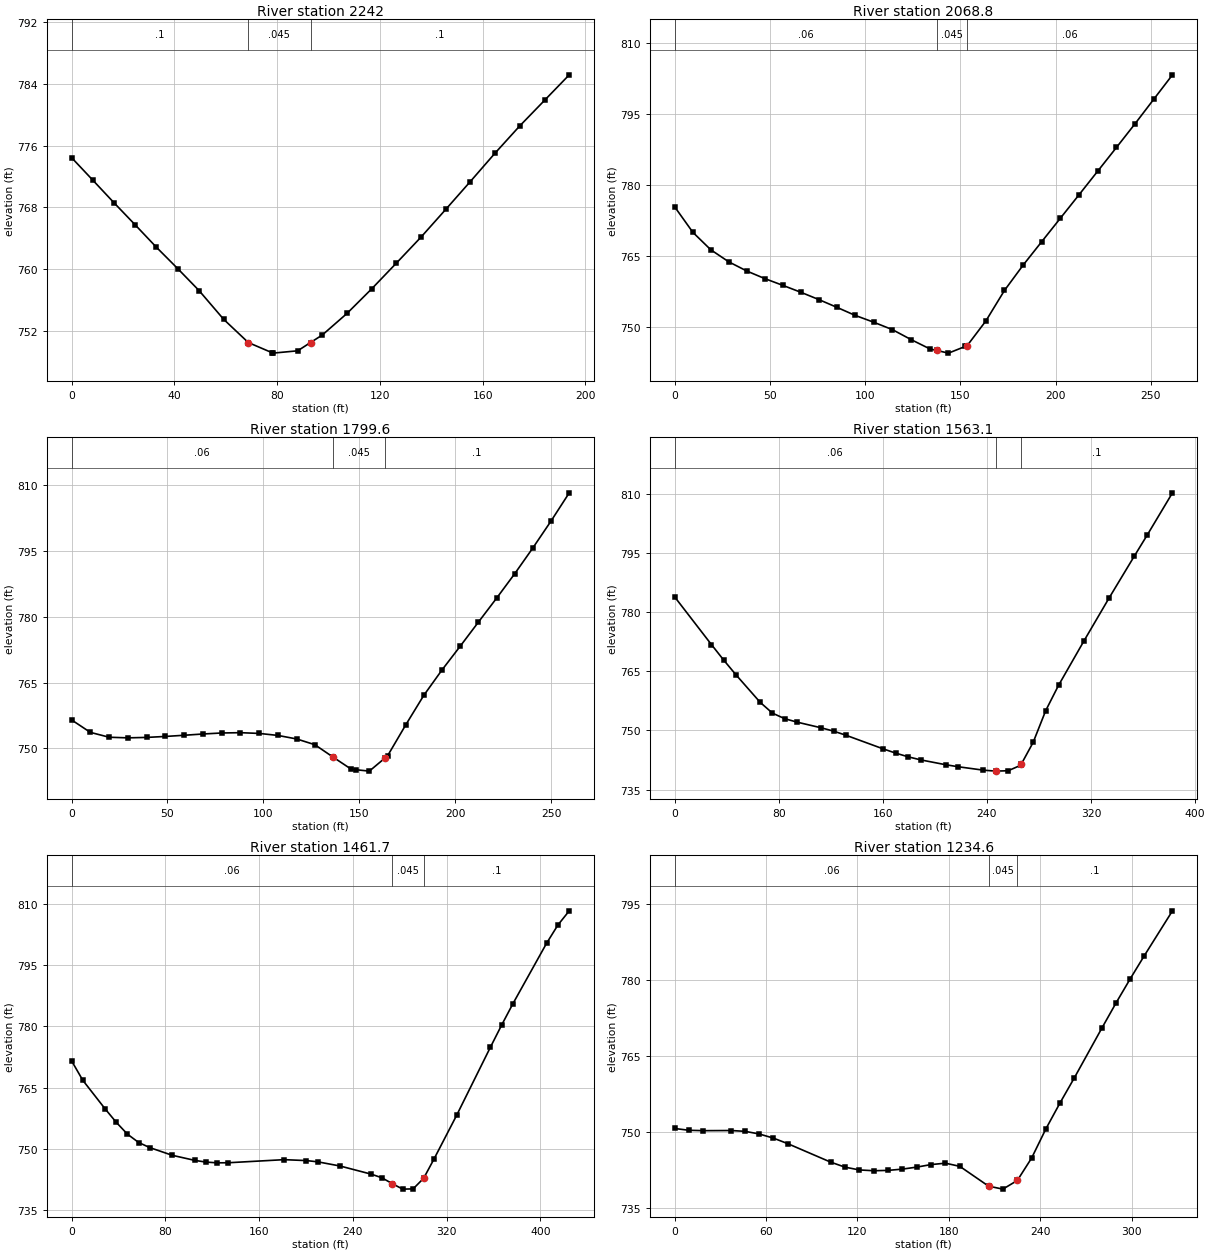
Type RM Length L Ch R = 1 ,2242    ,172.7,173.2,174
XS GIS Cut Line= 4
     1588028.249      307619.195     1588071.217      307594.455
     1588118.092      307546.278     1588151.946      307477.268
#Sta/Elev= 24
       0  774.44     8.3  771.51    16.5   768.6    24.8  765.72      33  762.84
    41.3  760.07    49.6  757.23    59.2   753.5    68.8  750.49      78  749.18
    78.4  749.12      88  749.42      93  750.49    97.6  751.47   107.2  754.26
   116.8  757.44   126.4  760.77     136  764.14   145.6  767.72   155.2  771.34
   164.8  775.01   174.4  778.53   184.1  781.86   193.7  785.16
#Mann= 3 , 0 , 0
       0      .1       0    68.8    .045       0      93      .1       0
Bank Sta=68.8,93
XS Rating Curve= 0 ,0
Exp/Cntr=0.3,0.1

Type RM Length L Ch R = 1 ,2068.8  ,265.5,269.2,272.4
XS GIS Cut Line= 3
     1588095.957      307731.174     1588189.707      307718.153
     1588309.499      307602.268
#Sta/Elev= 30
       0  775.37     9.5  770.02    18.9  766.34    28.4  763.78    37.9  761.84
    47.3  760.25    56.8  758.82    66.2  757.37    75.7  755.82    85.2  754.18
    94.6  752.51   104.4  751.06   114.3  749.48   124.1  747.38   133.9  745.43
   137.6  745.09   143.7  744.53   152.6  745.96   153.5   746.1   163.3   751.3
   173.1  757.76   182.9   763.1   192.7  768.07   202.5  773.02   212.3  777.97
   222.1  782.95   231.9  787.93   241.7  792.95   251.5  798.11   261.3  803.25
#Mann= 3 , 0 , 0
       0     .06       0   137.6    .045       0   153.5     .06       0
Bank Sta=137.6,153.5
XS Rating Curve= 0 ,0
Exp/Cntr=0.3,0.1

Type RM Length L Ch R = 1 ,1799.6  ,237.2,236.5,233.3
XS GIS Cut Line= 3
     1588257.415      307906.955     1588374.603      307900.445
     1588490.488      307818.414
#Sta/Elev= 30
       0  756.51     9.8  753.66    19.6  752.55    29.3  752.41    39.1  752.51
    48.9  752.73    58.7     753    68.5  753.29    78.2  753.52      88  753.59
    97.8  753.42   107.6  752.96   117.4  752.15   126.8  750.85   136.3  748.02
   145.8  745.25   148.2  745.14   155.2  744.82   163.2  747.75   164.7   748.3
   174.2  755.38   183.6  762.11   193.1  767.91   202.6  773.33     212  778.78
   221.5  784.25     231  789.86   240.4  795.71   249.9  801.86   259.4   808.3
#Mann= 3 , 0 , 0
       0     .06       0   136.3    .045       0   163.2      .1       0
Bank Sta=136.3,163.2
XS Rating Curve= 0 ,0
Exp/Cntr=0.3,0.1

Type RM Length L Ch R = 1 ,1563.1  ,109.4,101.4,95.7
XS GIS Cut Line= 4
     1588287.363      308143.935     1588417.571      308162.164
     1588532.155      308074.924     1588581.634      307979.872
#Sta/Elev= 30
       0   783.8    28.2  771.74    37.6  767.82      47   764.1    65.7  757.09
    75.1  754.36    84.5  752.96    93.9  752.09   112.7  750.63   122.1   749.8
   131.5  748.77   160.3  745.29   169.9  744.22   179.5  743.28   189.1  742.51
   208.3  741.28   217.9  740.77   237.1  739.91   246.7  739.66   256.3  739.76
   265.9  741.14   266.4  741.44   275.5  746.95   285.2  755.03     295   761.4
   314.5  772.64   333.9  783.57   353.4  794.24   363.2  799.52   382.6  810.22
#Mann= 3 , 0 , 0
       0     .06       0   246.7    .045       0   266.4      .1       0
Bank Sta=246.7,266.4
XS Rating Curve= 0 ,0
Exp/Cntr=0.3,0.1

Type RM Length L Ch R = 1 ,1461.7  ,231.2,227.1,222.9
XS GIS Cut Line= 4
     1588515.228      308432.997     1588556.894      308207.737
     1588599.863      308140.028     1588632.415      308029.351
#Sta/Elev= 30
       0  771.58     9.6   766.8    28.6   759.8    38.2  756.47    47.7  753.58
    57.3  751.53    66.8  750.28    85.9   748.4     105  747.16   114.5  746.74
   124.1  746.55   133.6  746.57   181.4  747.33   200.4   747.1     210   746.8
   229.1  745.77   255.8  743.76   264.7  742.89   273.6  741.45   282.5   740.1
   291.4  740.16   300.4  742.77   309.3  747.53   328.5  758.19   357.3  774.89
     367  780.39   376.6  785.62   405.4  800.48     415  804.92   424.6  808.37
#Mann= 3 , 0 , 0
       0     .06       0   273.6    .045       0   300.4      .1       0
Bank Sta=273.6,300.4
XS Rating Curve= 0 ,0
Exp/Cntr=0.3,0.1

Type RM Length L Ch R = 1 ,1234.6  ,126.7,128.1,129.6
XS GIS Cut Line= 4
     1588694.481      308438.639     1588737.204       308390.13
     1588803.856      308223.796     1588858.544      308161.296
#Sta/Elev= 30
       0   750.6     9.2  750.25    18.5  750.17    36.9   750.2    46.2  750.04
    55.4  749.52    64.6  748.72    74.1  747.62   102.4  743.96   111.8  742.97
   121.2  742.42   130.7  742.26   140.1  742.33   149.5  742.58     159  742.98
   168.4  743.48   177.8  743.75   187.2  743.13   206.1  739.22   215.5  738.63
     225  740.34   234.4  744.77   243.8  750.55   253.1  755.68   262.3  760.52
   280.7  770.51     290  775.47   299.2  780.17   308.4  784.71   326.9  793.57
#Mann= 3 , 0 , 0
       0     .06       0   206.1    .045       0     225      .1       0
Bank Sta=206.1,225
XS Rating Curve= 0 ,0
Exp/Cntr=0.3,0.1

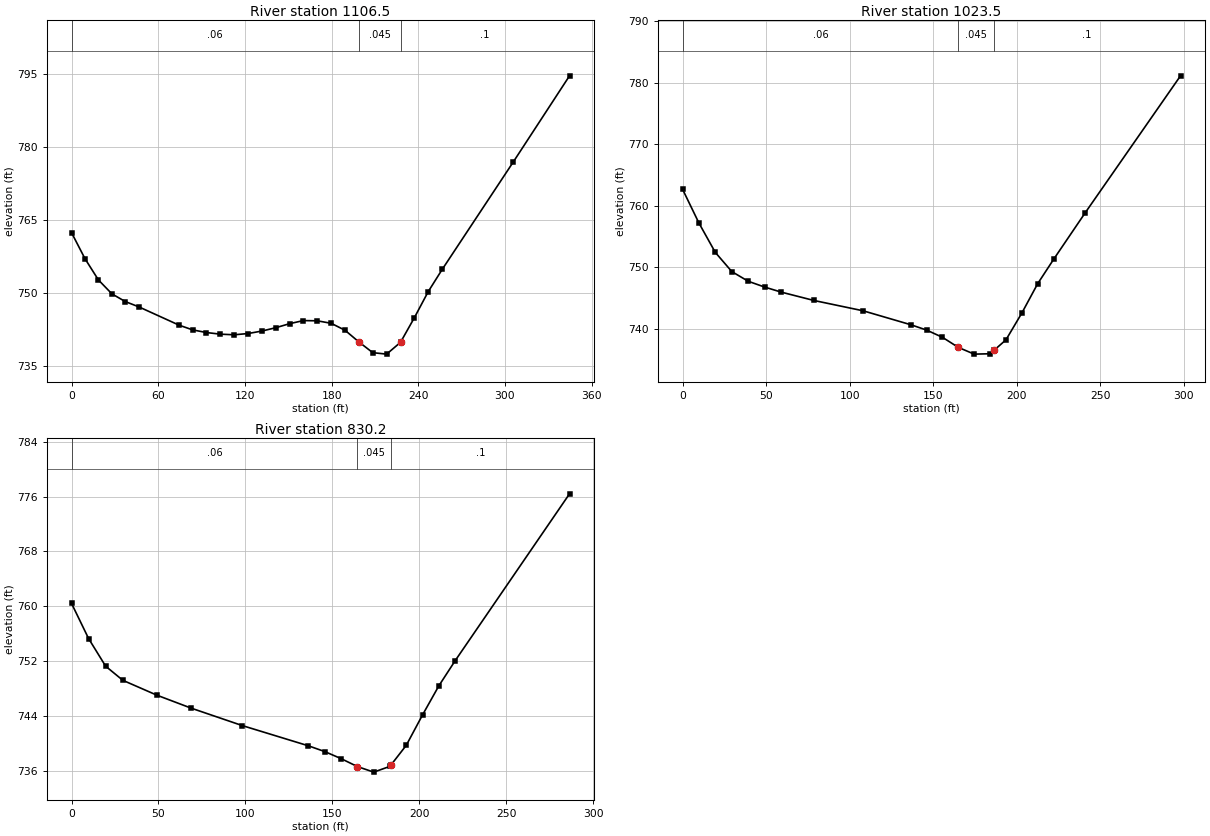
Type RM Length L Ch R = 1 ,1106.5  ,83.4,83.1,82.4
XS GIS Cut Line= 4
     1588806.894      308492.893     1588852.467       308422.58
      1588922.78      308275.445     1588939.707      308179.091
#Sta/Elev= 28
       0  762.34     9.3     757    18.6  752.64    27.9  749.79    37.2   748.2
    46.6  747.11    74.5  743.35    83.8  742.39    93.4  741.84     103  741.51
   112.6  741.38   122.2  741.64   131.8  742.15   141.3  742.83   150.9  743.66
   160.5   744.3   170.1  744.25   179.7  743.74   189.3  742.31   198.9  739.91
   208.5  737.71   218.1  737.41   227.7  739.83   237.3  744.89   246.9  750.25
   256.6  754.82   305.6  776.79   344.7  794.55
#Mann= 3 , 0 , 0
       0     .06       0   198.9    .045       0   227.7      .1       0
Bank Sta=198.9,227.7
XS Rating Curve= 0 ,0
Exp/Cntr=0.3,0.1

Type RM Length L Ch R = 1 ,1023.5  ,192.3,193.2,193
XS GIS Cut Line= 3
     1588950.124      308517.632     1588951.426       308409.56
     1589029.551      308236.382
#Sta/Elev= 22
       0  762.67     9.8  757.18    19.6  752.41    29.5  749.29    39.3  747.72
    49.1  746.78      59  745.96    78.6   744.6   108.1  742.92   136.6  740.66
   146.1  739.79   155.6  738.61   165.1  736.97   174.6  735.88   184.1  735.94
   186.4  736.49   193.6   738.2   203.1  742.55   212.6  747.33   222.1  751.27
   241.1  758.87   298.1   781.1
#Mann= 3 , 0 , 0
       0     .06       0   165.1    .045       0   186.4      .1       0
Bank Sta=165.1,186.4
XS Rating Curve= 0 ,0
Exp/Cntr=0.3,0.1

Type RM Length L Ch R = 1 ,830.2   ,251.2,256.9,263.7
XS GIS Cut Line= 4
      1589079.03       308547.58     1589135.019      308455.132
      1589172.78      308379.612     1589200.124      308289.768
#Sta/Elev= 19
       0   760.4     9.8  755.28    19.6  751.25    29.5  749.19    49.1  747.02
    68.8  745.13    98.3  742.58   136.2  739.64   145.6   738.8     155  737.77
   164.4  736.61   173.8   735.8   183.1  736.64   183.8  736.87   192.5  739.71
   201.9  744.16   211.3  748.41   220.7  752.08   286.4  776.39
#Mann= 3 , 0 , 0
       0     .06       0   164.4    .045       0   183.8      .1       0
Bank Sta=164.4,183.8
XS Rating Curve= 0 ,0
Exp/Cntr=0.3,0.1