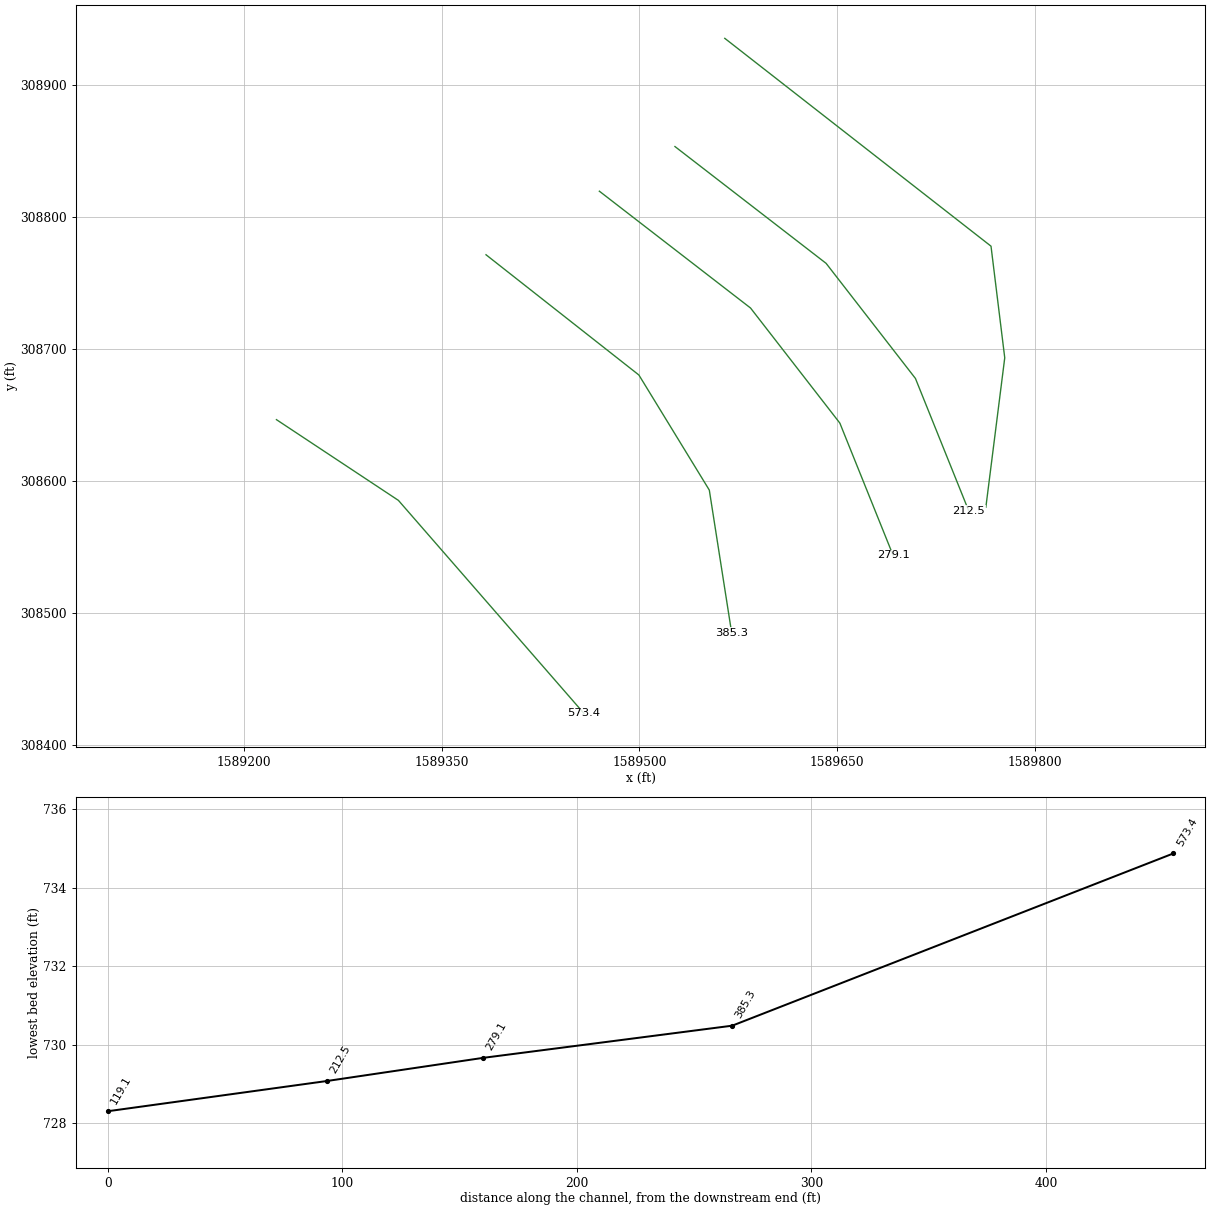
HEC-RAS study SHORTRN.prj: SHORTRN

--- SHORTRN.g02 (geometry) --- (continued)

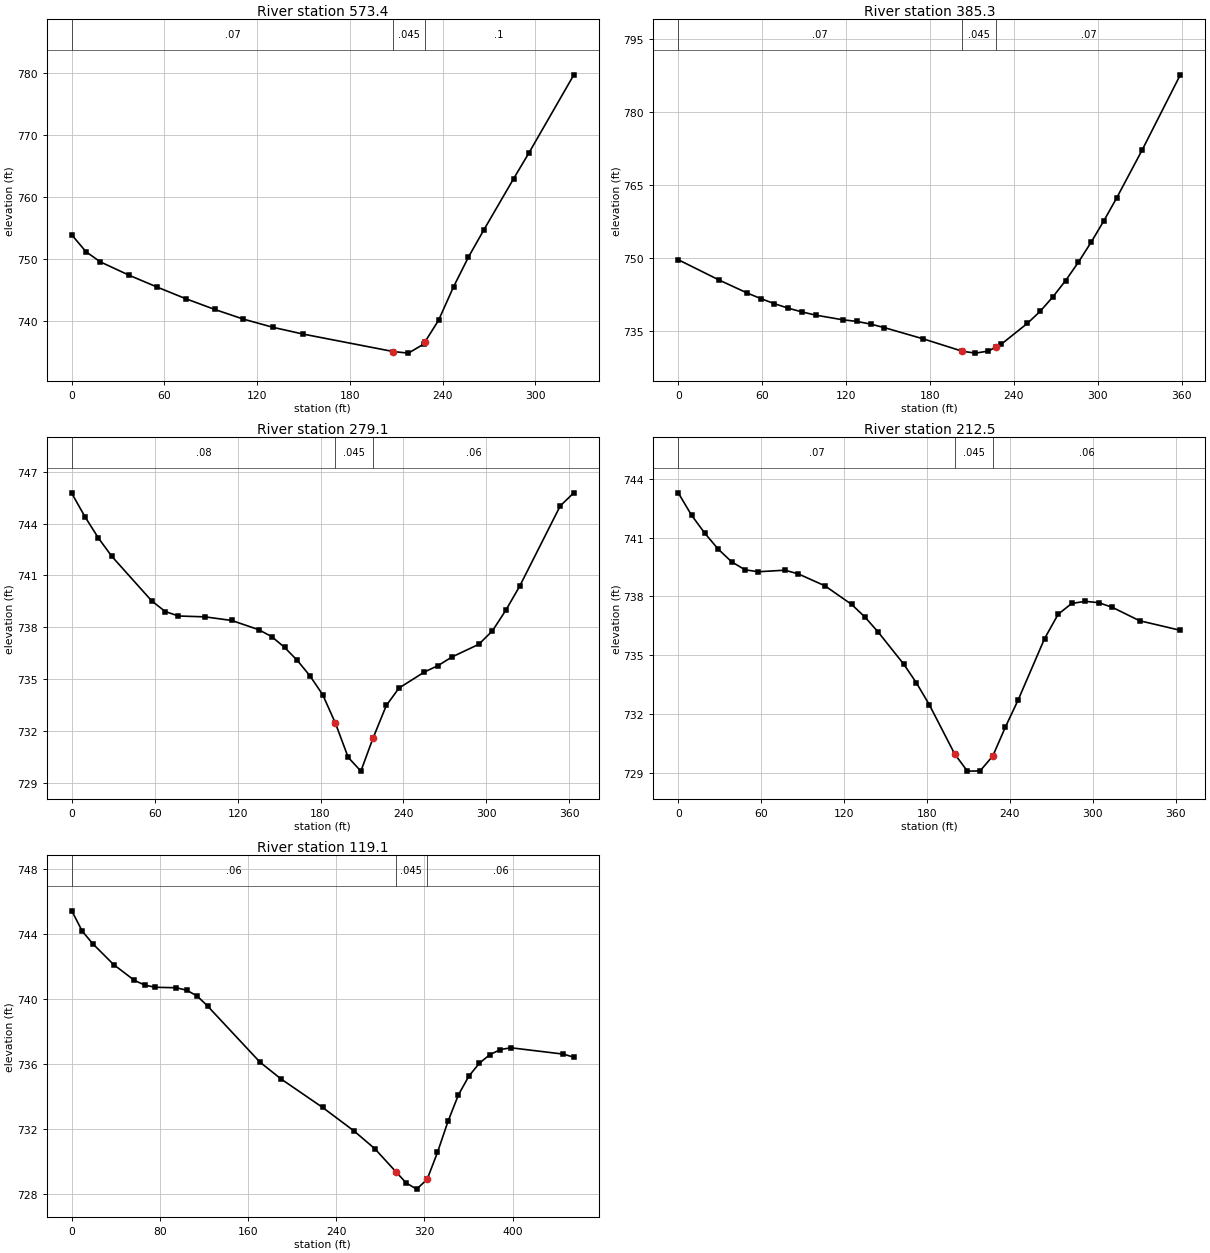
Type RM Length L Ch R = 1 ,573.4   ,191.8,188.1,184.3
XS GIS Cut Line= 3
     1589224.863      308646.539     1589317.311      308585.341
     1589457.936      308423.882
#Sta/Elev= 21
       0  753.96     9.2  751.24    18.5   749.6      37  747.46    55.4  745.52
    73.9  743.65    92.4  741.94   110.9  740.38   130.3  739.04   149.8  737.95
   208.2  735.13   217.9  734.88   227.7  736.32   228.4   736.6   237.4  740.17
   247.1  745.56   256.8  750.39   266.6   754.7     286  763.02   295.8  767.13
     325  779.78
#Mann= 3 , 0 , 0
       0     .07       0   208.2    .045       0   228.4      .1       0
Bank Sta=208.2,228.4
XS Rating Curve= 0 ,0
Exp/Cntr=0.3,0.1

Type RM Length L Ch R = 1 ,385.3   ,103.7,106.2,108.7
XS GIS Cut Line= 4
     1589383.717      308771.539     1589499.603      308680.393
     1589552.988      308593.153     1589569.915       308485.08
#Sta/Elev= 28
       0  749.67    29.5  745.46    49.1  742.86      59  741.69    68.8  740.64
    78.6  739.72    88.5  738.95    98.3  738.29     118  737.32   127.8     737
   137.6  736.45   147.4  735.73   175.3  733.41   203.2  730.88   212.5  730.49
   221.8  730.91   227.6   731.8   231.1  732.33   249.7   736.6   258.8  739.05
   267.9  742.02   277.1   745.4   286.2  749.15   295.3  753.25   304.4  757.65
   313.5  762.31   331.8  772.19   359.1  787.63
#Mann= 3 , 0 , 0
       0     .07       0   203.2    .045       0   227.6     .07       0
Bank Sta=203.2,227.6
XS Rating Curve= 0 ,0
Exp/Cntr=0.3,0.1

Type RM Length L Ch R = 1 ,279.1   ,66.6,66.6,67.4
XS GIS Cut Line= 4
     1589469.655      308819.716     1589584.238      308731.174
     1589651.946      308643.935     1589692.311      308543.674
#Sta/Elev= 30
       0  745.75     9.6  744.39    19.3  743.16      29   742.1    57.9  739.52
    67.6  738.91    77.2  738.65    96.5   738.6   115.8  738.39   135.2  737.86
   144.8  737.45     154  736.83   163.2  736.08   172.4  735.18   181.6  734.09
   190.8  732.44     200  730.47   209.2  729.67   217.9  731.56   227.6  733.47
   236.8  734.48   255.2  735.41   265.1  735.78   274.9  736.27   294.5  737.01
   304.4  737.79   314.2     739     324  740.36   353.5  745.03   363.3  745.78
#Mann= 3 , 0 , 0
       0     .08       0   190.8    .045       0   217.9     .06       0
Bank Sta=190.8,217.9
XS Rating Curve= 0 ,0
Exp/Cntr=0.3,0.1

Type RM Length L Ch R = 1 ,212.5   ,105.7,93.4,80.4
XS GIS Cut Line= 4
     1589526.946       308853.57      1589641.53      308765.028
     1589709.238      308677.789     1589749.603      308577.528
#Sta/Elev= 30
       0  743.29     9.6  742.15    19.3  741.22      29  740.41    38.6  739.77
    48.3  739.36    57.9  739.26    77.2  739.34    86.9  739.15   106.2  738.54
   125.5  737.59   135.2  736.94   144.8  736.17   163.2  734.54   172.4  733.58
   181.6  732.48     200  729.96   209.2  729.08   218.4  729.09   227.6  729.85
   236.8  731.34     246  732.72   265.1  735.85   274.9  737.09   284.7  737.64
   294.5  737.75   304.4  737.68   314.2  737.44   333.8  736.76   363.3  736.27
#Mann= 3 , 0 , 0
       0     .07       0     200    .045       0   227.6     .06       0
Bank Sta=200,227.6
XS Rating Curve= 0 ,0
Exp/Cntr=0.3,0.1

Type RM Length L Ch R = 1 ,119.1   ,132.6,119.1,105.7
XS GIS Cut Line= 4
     1589564.707      308935.601      1589766.53      308778.049
     1589776.946      308693.414     1589762.624      308580.132
#Sta/Elev= 30
       0  745.42     9.5  744.17      19   743.4    37.9  742.12    56.9  741.14
    66.4  740.85    75.9  740.72    94.8  740.69   104.3  740.54   113.8  740.18
   123.3  739.56   170.7  736.12   189.7  735.09   227.6  733.33     256  731.89
     275  730.79   293.9  729.39   303.4  728.69   312.9  728.31   322.4  728.91
   331.8  730.57   341.3  732.47   350.8  734.11   360.3  735.26   369.9  736.06
   379.4  736.58   388.9  736.89   398.4     737     446  736.61   455.5  736.42
#Mann= 3 , 0 , 0
       0     .06       0   293.9    .045       0   322.4     .06       0
Bank Sta=293.9,322.4
XS Rating Curve= 0 ,0
Exp/Cntr=0.3,0.1